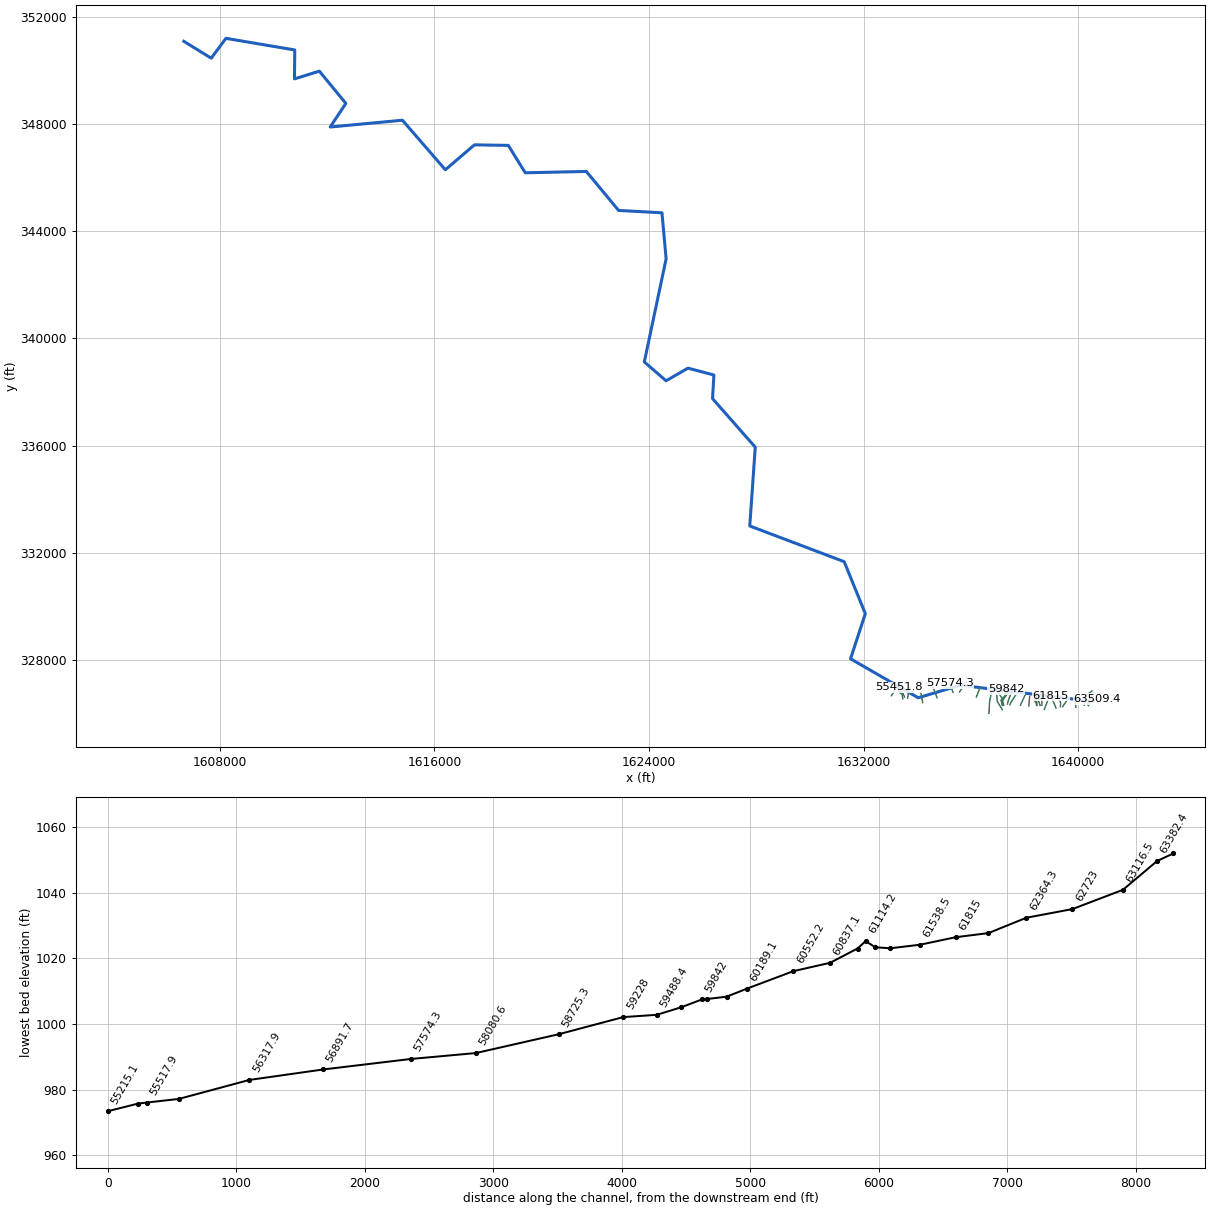
--- stfrktwl1.prj (project) ---

Proj Title=stfrktwl1
Current Plan=p01
Default Exp/Contr=0,0
English Units
Geom File=g01
Flow File=f01
Plan File=p01
BEGIN DESCRIPTION:
END DESCRIPTION:
DSS Export Rating Curves= 0
DSS Export Rating Curve Sorted= 0
DSS Export Volume Flow Curves= 0
DXF OffsetX= 0
DXF OffsetY= 0
DXF ScaleX= 0
DXF ScaleY= 0

--- stfrktwl1.p01 (plan) ---

Plan Title=Approximate Study - 100yr
Program Version=4.00
Geom File=g01
Flow File=f01
Subcritical Flow
K Sum by GR= 0
Std Step Tol= 0.01
Critical Tol= 0.01
Num of Std Step Trials= 20
Max Error Tol= 0.3
Flow Tol Ratio= 0.001
Split Flow NTrial= 30
Split Flow Tol= 0.02
Split Flow Ratio= 0.02
Log Output Level= 0
Friction Slope Method= 1
Unsteady Friction Slope Method= 2
Unsteady Bridges Friction Slope Method= 1
Parabolic Critical Depth
Global Vel Dist= 0 , 0 , 0
Global Log Level= 0
CheckData=True
Encroach Param=-1 ,0,0, 0
Run HTab= 0
Run UNet= 0
Run PostProcess= 0
Run WQNet= 0
UNET Theta= 0
UNET Theta Warmup= 0
UNET ZTol= 0
UNET ZSATol= 0
UNET MxIter= 0
UNET MaxInSteps= 0
UNET DtIC= 0
UNET DtMin= 0
UNET MaxCRTS= 0
UNET WFStab= 0
UNET SFStab= 0
UNET WFX= 1
UNET SFX= 1
UNET DSS MLevel= 1
UNET DZMax Abort= 0
UNET Convert EG Bridges= 0
UNET Use Existing IB Tables= 0
UNET Froude Reduction=False
UNET Froude Limit= 0
UNET Froude Power= 0
UNET Time Slicing=0,0, 5
Write IC File= 0
Echo Input=False
Echo Output=False
Write Detailed= 0
Detailed Automatic Start=False, 0
WQ ULTIMATE=-1
WQ Max Comp Step=1HOUR
WQ Output Interval=15MIN
WQ Output Selected Increments= 0
WQ Output face flow=0
WQ Output face velocity=0
WQ Output face area=0
WQ Output face dispersion=0
WQ Output cell volume=0
WQ Output cell surface area=0
WQ Output cell continuity=0
WQ Output face conc=0
WQ Output face dconc_dx=0
WQ Output face courant=0
WQ Output face peclet=0
WQ Output face adv mass=0
WQ Output face disp mass=0
WQ Output cell mass=0
WQ Output cell source sink temp=0
WQ Output cell source sink nsm=0
WQ Output MaxMinRange=-1
WQ Daily Max Min Mean=-1
WQ Daily Range=0
WQ Daily Time=0
WQ Create Restart=0
WQ Fixed Restart=0
WQ System Summary=False
Sorting and Armoring Iterations= 10
XS Update Threshold= 0.02
Hydraulics Update Threshold= 0.02
Energy Slope Method= 1
Volume Change Method= 0
XS Weighting Method= 0
Number of US Weighted Cross Sections= 1
Number of DS Weighted Cross Sections= 1
Upstream XS Weight=0.25
Main XS Weight=0.5
Downstream XS Weight=0.25
Number of DS XS's Weighted with US Boundary= 1
Upstream Boundary Weight= 1
Weight of XSs Associated with US Boundary= 0
Number of US XS's Weighted with DS Boundary= 1
Downstream Boundary Weight= 0.5
Weight of XSs Associated with DS Boundary= 0.5
Sediment Output Level= 4
Mass or Volume Output= 0
Output Increment Type= 1
Profile and TS Output Increment= 10
XS Output Flag= 0
XS Output Increment= 10
Disregard all LS=0
Disregard all Conn=0
Disregard all Breaches=0
Disregard all Pumps=0

--- stfrktwl1.f01 (steady flow) ---

Flow Title=USGS Regression Equation
Program Version=4.00
Number of Profiles= 1
Profile Names=P100yr
River Rch & RM=stfrktwl1,Main            ,63509.4
     387
River Rch & RM=stfrktwl1,Main            ,61538.5
     402
River Rch & RM=stfrktwl1,Main            ,60032.1
     460
River Rch & RM=stfrktwl1,Main            ,59488.4
     540
River Rch & RM=stfrktwl1,Main            ,59228
     685
River Rch & RM=stfrktwl1,Main            ,55769.2
     740
River Rch & RM=stfrktwl1,Main            ,52668.5
     822
River Rch & RM=stfrktwl1,Main            ,50135.6
     915
River Rch & RM=stfrktwl1,Main            ,49881
     964
River Rch & RM=stfrktwl1,Main            ,49055.3
    1069
River Rch & RM=stfrktwl1,Main            ,46382
    1097
River Rch & RM=stfrktwl1,Main            ,44439.4
    1216
River Rch & RM=stfrktwl1,Main            ,42108.8
    1258
River Rch & RM=stfrktwl1,Main            ,38738.9
    1396
River Rch & RM=stfrktwl1,Main            ,36422.9
    1499
River Rch & RM=stfrktwl1,Main            ,33789.3
    1665
River Rch & RM=stfrktwl1,Main            ,25901.8
    1849
River Rch & RM=stfrktwl1,Main            ,21602.2
    2046
River Rch & RM=stfrktwl1,Main            ,18492.3
    2261
River Rch & RM=stfrktwl1,Main            ,15324.9
    2482
River Rch & RM=stfrktwl1,Main            ,11141.2
    2598
River Rch & RM=stfrktwl1,Main            ,10644.7
    3101
River Rch & RM=stfrktwl1,Main            ,322
    3396
Boundary for River Rch & Prof#=stfrktwl1,Main            , 1
Up Type= 0
Dn Type= 3
Dn Slope=0.001802
DSS Import GetInterval= 0
DSS Import GetPeak= 0
DSS Import FillOption= 0

--- stfrktwl1.g01 (geometry) ---

Geom Title=USGS 3m DEM
Program Version=4.00

River Reach=stfrktwl1       ,Main
Reach XY= 30
     1640543.173      326467.064     1635613.779      327073.092
     1634037.523      326605.908     1631515.219      328057.348
      1632065.65      329741.426     1631278.707      331678.479
     1627756.762      333010.437     1627961.817      335947.503
     1626369.143      337758.117     1626420.298      338637.891
     1625453.524      338893.921     1624636.451      338422.143
     1623824.797      339126.647     1624638.547      342967.723
     1624482.963      344684.799     1622866.707      344773.477
     1621662.089      346225.965     1619385.821      346176.548
     1618752.386      347197.921      1617491.53      347217.932
     1616405.985      346289.144     1614805.186       348136.23
     1612110.888      347883.026      1612695.41      348763.182
      1611707.39      349965.574     1610780.364       349676.94
      1610790.56      350754.755     1608224.246      351188.773
     1607675.836      350448.637     1606654.538      351077.618

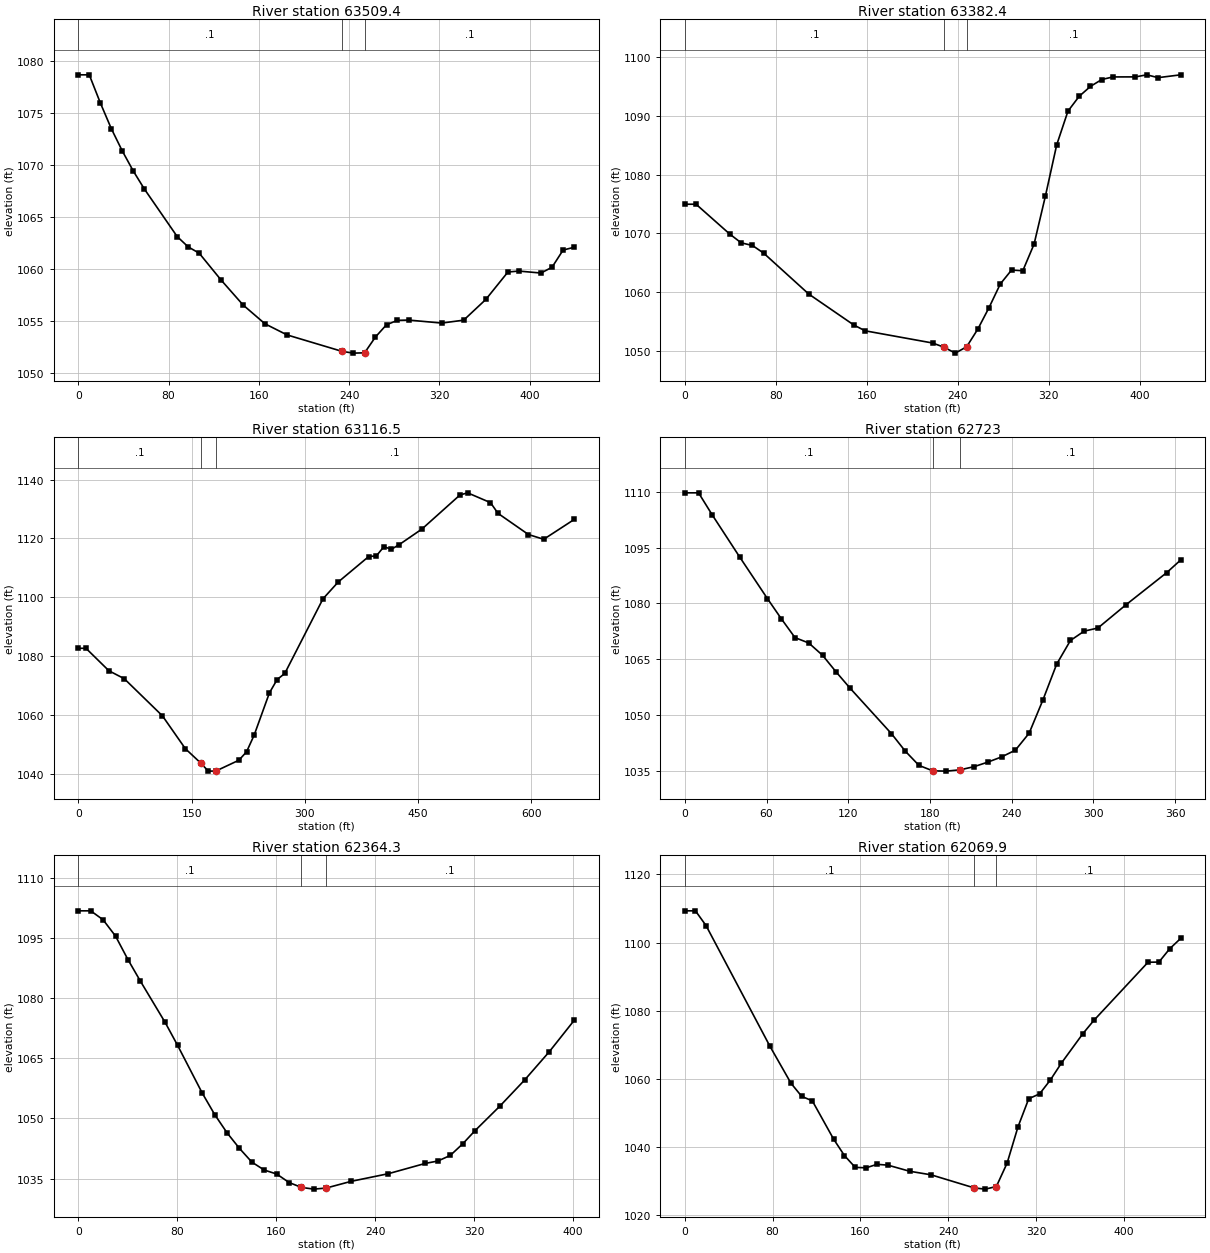
Type RM Length L Ch R = 1 ,63509.4 ,108.7,127.1,144.3
XS GIS Cut Line= 3
     1640385.758      326310.942     1640458.734      326459.424
     1640714.218      326558.201
#Sta/Elev= 30
       0  1078.7     9.7  1078.7    19.5    1076    29.2 1073.53    38.9 1071.39
    48.7 1069.45    58.4 1067.74    87.6 1063.15    97.3 1062.16   107.1 1061.55
   126.5 1058.97     146 1056.57   165.4 1054.76     185 1053.69   233.7 1052.11
   243.7 1051.94   253.7 1051.97   263.3 1053.49   273.1 1054.67   282.8 1055.09
   292.6 1055.12     322 1054.83   341.5 1055.11   361.1  1057.1   380.7 1059.74
   390.4 1059.83     410 1059.64   419.8  1060.2   429.6 1061.85   439.4 1062.12
#Mann= 3 , 0 , 0
       0      .1       0   233.7    .045       0   253.7      .1       0
Bank Sta=233.7,253.7
XS Rating Curve= 0 ,0
Exp/Cntr=0.3,0.1

Type RM Length L Ch R = 1 ,63382.4 ,252.5,265.8,273.7
XS GIS Cut Line= 2
     1640355.023      326349.814      1640538.14      326745.584
#Sta/Elev= 30
       0 1074.97     9.9 1074.97    39.6 1069.88    49.6  1068.4    59.5 1067.95
    69.4 1066.64     109 1059.69   148.7 1054.41   158.6 1053.43     218 1051.35
   227.9 1050.64   237.9 1049.63   247.9 1050.71   257.7 1053.71   267.6 1057.38
   277.5  1061.4   287.4 1063.77   297.3 1063.65   307.2 1068.18   317.1  1076.3
   327.1 1085.07     337 1090.81   346.9 1093.34   356.8 1095.02   366.7 1096.19
   376.6 1096.63   396.4 1096.64   406.3 1096.99   416.3 1096.51   436.1 1096.99
#Mann= 3 , 0 , 0
       0      .1       0   227.9    .045       0   247.9      .1       0
Bank Sta=227.9,247.9
XS Rating Curve= 0 ,0
Exp/Cntr=0.3,0.1

Type RM Length L Ch R = 1 ,63116.5 ,387.7,393.5,399.3
XS GIS Cut Line= 3
     1640229.631      326328.846     1640256.862      326651.714
     1640517.823      326857.929
#Sta/Elev= 30
       0 1082.64    10.1 1082.64    40.5 1074.99    60.8  1072.3   111.4 1059.65
   141.8 1048.47   162.1 1043.61   172.1 1040.86   182.1 1040.89   212.6 1044.57
   222.8 1047.44   232.9 1053.15   253.1 1067.51   263.3 1072.01   273.4 1074.09
     324 1099.47   344.2 1105.19   384.5 1113.84   394.6 1114.05   404.6 1117.17
   414.7 1116.33   424.8 1117.87     455 1123.19   505.4 1134.78   515.5 1135.51
   545.8 1132.17   555.8 1128.52   596.1 1121.32   616.3 1119.71   656.6 1126.44
#Mann= 3 , 0 , 0
       0      .1       0   162.1    .045       0   182.1      .1       0
Bank Sta=162.1,182.1
XS Rating Curve= 0 ,0
Exp/Cntr=0.3,0.1

Type RM Length L Ch R = 1 ,62723   ,374.7,358.7,342.7
XS GIS Cut Line= 2
     1639919.563      326252.089     1639847.496      326608.884
#Sta/Elev= 30
       0  1109.7    10.1  1109.7    20.2 1103.74    40.4 1092.41    60.7 1081.28
    70.8 1075.92    80.9 1070.83      91 1069.39   101.1  1066.1   111.2 1061.57
   121.3 1057.27   151.7 1045.05   161.8 1040.38   171.9 1036.53   182.1 1035.06
   192.1 1034.99   202.1 1035.34   212.3 1036.18   222.4  1037.4   232.6 1038.81
   242.7 1040.62   252.8 1045.18   262.9 1054.09     273 1063.71   283.1 1070.06
   293.2 1072.57   303.3 1073.41   323.6 1079.56   353.9 1088.31     364 1091.66
#Mann= 3 , 0 , 0
       0      .1       0   182.1    .045       0   202.1      .1       0
Bank Sta=182.1,202.1
XS Rating Curve= 0 ,0
Exp/Cntr=0.3,0.1

Type RM Length L Ch R = 1 ,62364.3 ,277.7,294.4,310.5
XS GIS Cut Line= 2
     1639423.948      326273.565     1639647.422      326606.424
#Sta/Elev= 30
       0 1101.86      10 1101.86      20 1099.63    30.1 1095.54    40.1 1089.69
    50.1 1084.34    70.2 1073.98    80.2 1068.29   100.2 1056.33   110.3 1050.95
   120.3 1046.39   130.3 1042.52   140.3  1039.1   150.3 1037.12   160.4 1036.12
   170.4    1034   180.4 1032.78   190.4 1032.35   200.4 1032.62   220.5 1034.29
   250.6  1036.2   280.6 1038.78   290.7 1039.37   300.7 1040.76   310.7 1043.63
   320.7 1046.94   340.8 1053.07   360.8 1059.59   380.9 1066.71   400.9  1074.5
#Mann= 3 , 0 , 0
       0      .1       0   180.4    .045       0   200.4      .1       0
Bank Sta=180.4,200.4
XS Rating Curve= 0 ,0
Exp/Cntr=0.3,0.1

Type RM Length L Ch R = 1 ,62069.9 ,252.2,254.9,257.5
XS GIS Cut Line= 3
     1639339.263      326271.213     1639348.672      326406.474
     1639252.226      326707.576
#Sta/Elev= 30
       0 1109.31     9.7 1109.31    19.4 1104.96    77.5 1069.63    96.8 1058.72
   106.5 1054.89   116.2 1053.57   135.6 1042.35   145.5 1037.51   155.3 1034.06
   165.2 1033.93   175.1 1034.95     185 1034.72   204.8 1032.93   224.5 1031.87
   263.9 1028.02   273.9 1027.68   283.9 1028.45   293.7 1035.32   303.6 1045.94
   313.4  1054.2   323.3 1055.62   333.2 1059.73   343.1 1064.62   362.8 1073.31
   372.7 1077.16   422.1 1094.23     432 1094.28   441.9  1098.2   451.8  1101.2
#Mann= 3 , 0 , 0
       0      .1       0   263.9    .045       0   283.9      .1       0
Bank Sta=263.9,283.9
XS Rating Curve= 0 ,0
Exp/Cntr=0.3,0.1

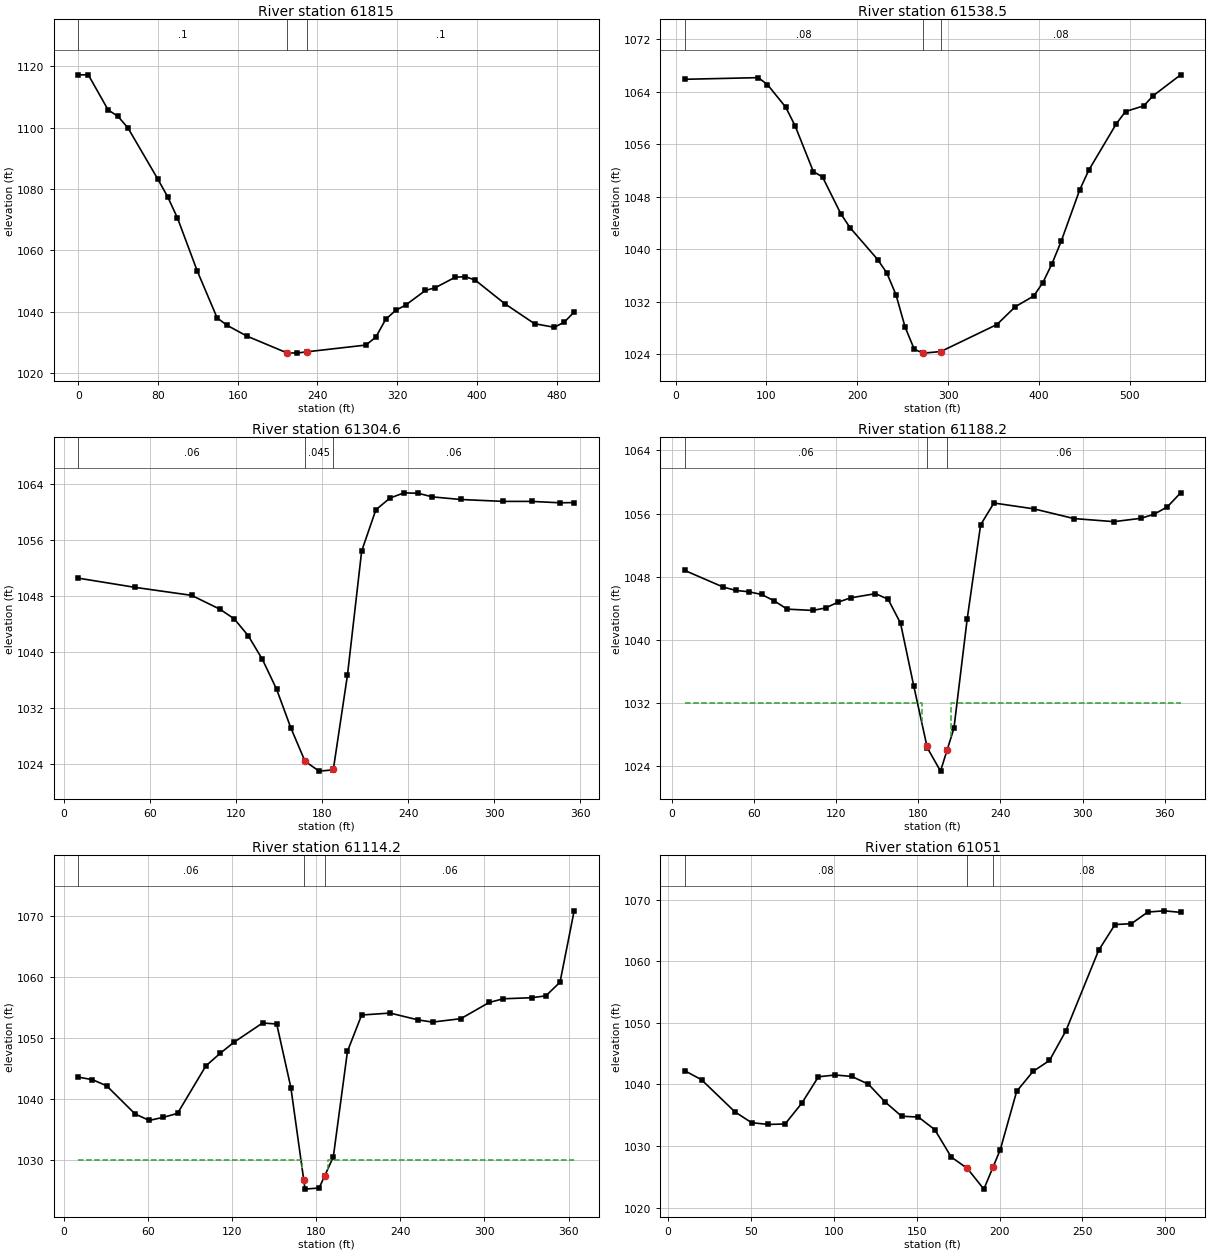
Type RM Length L Ch R = 1 ,61815   ,291.6,276.5,261.7
XS GIS Cut Line= 2
      1639176.95      326222.989     1638984.056        326681.7
#Sta/Elev= 30
       0 1117.18      10 1117.18    29.9 1105.74    39.8 1103.63    49.8 1099.87
    79.6 1083.27    89.6 1077.45    99.5 1070.48   119.4 1053.17   139.3 1037.91
   149.3  1035.5   169.2 1031.98     209 1026.56     219 1026.43     229 1026.85
   288.6 1029.06   298.6 1031.66   308.5 1037.47   318.5 1040.37   328.4 1042.08
   348.3 1046.86   358.3 1047.78   378.2 1051.17   388.1 1051.37   398.1 1050.29
     428 1042.54   457.8 1036.03   477.7 1034.85   487.7 1036.55   497.6 1039.83
#Mann= 3 , 0 , 0
       0      .1       0     209    .045       0     229      .1       0
Bank Sta=209,229
XS Rating Curve= 0 ,0
Exp/Cntr=0.3,0.1

Type RM Length L Ch R = 1 ,61538.5 ,225.9,233.9,241.6
XS GIS Cut Line= 2
     1638739.623      326170.954     1638937.222      326690.826
#Sta/Elev= 30
    10.1 1065.86      91 1066.11   101.1 1065.06   121.3  1061.6   131.5  1058.8
   151.7  1051.8   161.8 1050.98     182 1045.36   192.1 1043.26   222.5 1038.41
   232.6 1036.36   242.7 1033.04   252.8 1028.09   262.9 1024.72     2721024.206
     273 1024.15   292.11024.393   353.9 1028.51   374.1 1031.22   394.4 1032.85
   404.5  1034.9   414.6 1037.79   424.7  1041.2   444.9 1048.96     455 1052.01
   485.4 1059.09   495.5 1060.95   515.7 1061.82   525.8 1063.34   556.2 1066.54
#Mann= 3 , 0 , 0
    10.1     .08       0     272    .045       0   292.1     .08       0
Bank Sta=272,292.1
XS Rating Curve= 0 ,0
Exp/Cntr=0.3,0.1

Type RM Length L Ch R = 1 ,61304.6 ,116.2,116.4,116.6
XS GIS Cut Line= 2
     1638652.718      326329.186      1638638.17       326684.57
#Sta/Elev= 26
     9.9 1050.53    49.4 1049.22    88.9 1048.08   108.7  1046.1   118.6 1044.74
   128.4 1042.33   138.3 1038.95   148.2  1034.7   158.1 1029.21   167.8 1024.55
     168 1024.46   177.8 1023.05   187.7 1023.23   187.8 1023.37   197.6 1036.73
   207.5 1054.39   217.4 1060.26   227.2 1061.93   237.1 1062.68     247 1062.61
   256.9  1062.1   276.6 1061.73   306.3 1061.46     326 1061.46   345.8 1061.26
   355.7 1061.29
#Mann= 3 , 0 , 0
     9.9     .06       0   167.8    .045       0   187.8     .06       0
Bank Sta=167.8,187.8
XS Rating Curve= 0 ,0
Exp/Cntr=0.3,0.1

Type RM Length L Ch R = 1 ,61188.2 ,73.9,74,74.2
XS GIS Cut Line= 4
     1638586.906      326315.331     1638548.112       326420.63
     1638530.793      326472.587     1638520.402       326676.95
#Sta/Elev= 30
     9.4 1048.79    37.4 1046.69    46.8 1046.26    56.1 1046.09    65.5 1045.75
    74.8 1044.93    84.2 1043.89   102.9 1043.73   112.2 1044.04   121.3 1044.77
   130.5 1045.32   148.7 1045.85   157.9 1045.15     167 1042.11   176.7 1034.13
   186.2 1026.59   186.5 1026.35   196.2 1023.38     201 1026.04     206 1028.81
   215.7 1042.66   225.5 1054.57   235.2 1057.33   264.4 1056.59   293.7 1055.36
   322.9 1054.97   342.4 1055.39   352.1  1055.9   361.9 1056.84   371.6 1058.62
#Mann= 3 , 0 , 0
     9.4     .06       0   186.2    .045       0     201     .06       0
#XS Ineff= 2 , 0
       0     183    1032     204       0    1032
Permanent Ineff=
       F       F
Bank Sta=186.2,201
XS Rating Curve= 0 ,0
Exp/Cntr=0.3,0.1

Type RM Length L Ch R = 1 ,61114.2 ,63.3,63.2,63
XS GIS Cut Line= 3
      1638466.68      326316.227     1638455.733      326497.897
     1638444.786      326679.568
#Sta/Elev= 30
    10.1 1043.58    20.2 1043.16    30.3 1042.16    50.6 1037.55    60.7 1036.49
    70.8    1037    80.9 1037.64   101.1 1045.41   111.2 1047.45   121.3 1049.31
   141.6 1052.44   151.7 1052.28   161.8 1041.86     1711026.721   171.9 1025.24
     182 1025.43     1861027.446   192.1 1030.52   202.2 1047.81   212.3 1053.75
   232.6 1054.07   252.8 1052.94   262.9 1052.59   283.1 1053.15   303.3  1055.8
   313.4 1056.41   333.7 1056.58   343.8 1056.89   353.9 1059.12     364 1070.81
#Mann= 3 , 0 , 0
    10.1     .06       0     171    .045       0     186     .06       0
#XS Ineff= 2 , 0
       0     170    1030     188       0    1030
Permanent Ineff=
       F       F
Bank Sta=171,186
XS Rating Curve= 0 ,0
Exp/Cntr=0.3,0.1

Type RM Length L Ch R = 1 ,61051   ,216.6,213.9,211.3
XS GIS Cut Line= 4
     1638449.048      326327.108     1638437.964      326417.166
     1638395.013      326459.424       1638386.7      326617.373
#Sta/Elev= 30
    10.1 1042.22    20.2 1040.76    40.3 1035.55    50.4 1033.78    60.5  1033.5
    70.6 1033.57    80.7 1036.96    90.7 1041.24   100.8 1041.53   110.8  1041.3
   120.9 1040.03   130.9 1037.16   140.9 1034.83     151  1034.7   160.9 1032.65
   170.8 1028.21   180.5 1026.36   190.5 1022.99     1961026.546   200.4 1029.39
   210.3 1038.88   220.2 1042.12   230.1 1043.89     240 1048.71   259.7 1061.76
   269.6 1065.97   279.5 1066.11   289.4    1068   299.3  1068.2   309.2 1067.95
#Mann= 3 , 0 , 0
    10.1     .08       0   180.5    .045       0     196     .08       0
Bank Sta=180.5,196
XS Rating Curve= 0 ,0
Exp/Cntr=0.3,0.1

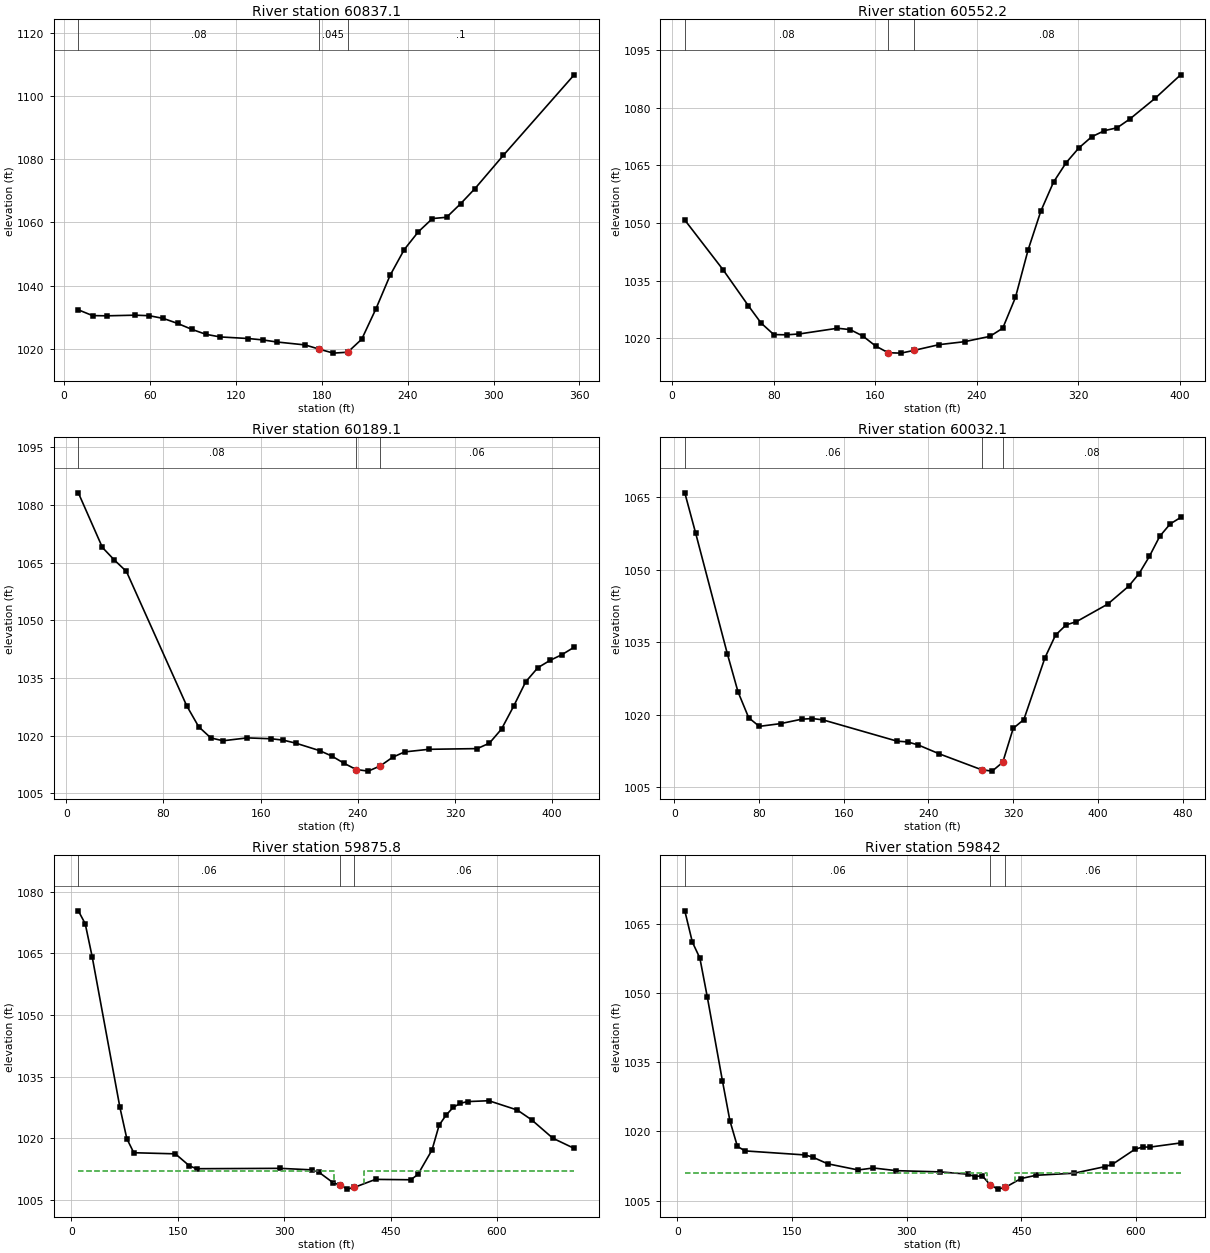
Type RM Length L Ch R = 1 ,60837.1 ,292.2,284.9,277.5
XS GIS Cut Line= 2
     1638164.259      326301.794     1638192.487         326657.
#Sta/Elev= 28
     9.9 1032.34    19.8 1030.51    29.7 1030.44    49.5 1030.64    59.4 1030.48
    69.3 1029.61    79.2 1028.04    89.1 1026.17      99 1024.59   108.9 1023.76
   128.7 1023.25   138.6 1022.82   148.5 1022.16   168.3 1021.23   178.1  1019.9
   188.1 1018.63   198.1 1018.92   207.9 1023.05   217.8 1032.64   227.7 1043.24
   237.6 1051.41   247.4 1057.02   257.3 1061.23   267.2 1061.63   277.1 1065.98
     287 1070.71   306.8 1081.23   356.3 1106.72
#Mann= 3 , 0 , 0
     9.9     .08       0   178.1    .045       0   198.1      .1       0
Bank Sta=178.1,198.1
XS Rating Curve= 0 ,0
Exp/Cntr=0.3,0.1

Type RM Length L Ch R = 1 ,60552.2 ,365.8,363.1,360.4
XS GIS Cut Line= 2
     1637849.606      326332.937     1638019.221      326695.796
#Sta/Elev= 30
      10 1050.76    40.1 1037.83    60.1 1028.43    70.1 1023.93    80.1 1020.93
    90.1 1020.87   100.1 1021.09   130.2 1022.58   140.2 1022.23   150.2 1020.56
   160.2 1017.97   170.2  1016.2   180.2  1016.1   190.2 1016.79   210.3 1018.31
   230.3 1019.08   250.3 1020.47   260.4 1022.59   270.4 1030.59   280.4 1043.01
   290.4 1053.08   300.4 1060.64   310.4 1065.72   320.4 1069.55   330.4 1072.43
   340.5 1074.04   350.5 1074.79   360.5 1077.07   380.5 1082.49   400.5 1088.58
#Mann= 3 , 0 , 0
      10     .08       0   170.2    .045       0   190.2     .08       0
Bank Sta=170.2,190.2
XS Rating Curve= 0 ,0
Exp/Cntr=0.3,0.1

Type RM Length L Ch R = 1 ,60189.1 ,152.8,157,161.2
XS GIS Cut Line= 3
     1637456.367      326343.063     1637495.185        326434.2
     1637669.087      326701.695
#Sta/Elev= 30
     9.9 1083.18    29.7 1068.97    39.6 1065.68    49.5 1062.72    99.1 1027.78
     109  1022.3     119  1019.4     129 1018.66   148.9 1019.41   168.9 1019.18
   178.8 1018.81   188.8 1018.05   208.7 1016.08   218.7 1014.66   228.7  1012.8
   238.6 1011.18   248.6 1010.76   258.6 1012.14   268.6 1014.36   278.5 1015.76
   298.5 1016.44   338.3 1016.62   348.3 1018.03   358.3 1021.71   368.3 1027.67
   378.2    1034   388.2 1037.67   398.2 1039.57   408.1 1041.08   418.1 1043.01
#Mann= 3 , 0 , 0
     9.9     .08       0   238.6    .045       0   258.6     .06       0
Bank Sta=238.6,258.6
XS Rating Curve= 0 ,0
Exp/Cntr=0.3,0.1

Type RM Length L Ch R = 1 ,60032.1 ,161.5,156.3,150.4
XS GIS Cut Line= 4
     1637366.652      326373.823     1637396.428      326500.867
     1637482.778      326724.187     1637559.203      326800.612
#Sta/Elev= 30
      10 1065.96    20.1 1057.73    50.2 1032.59    60.2 1024.76    70.3 1019.38
    80.3 1017.59   100.4 1018.16   120.4 1019.08   130.5 1019.21   140.5 1018.93
   210.3 1014.53   220.3 1014.37   230.3 1013.74   250.2  1011.9   290.1 1008.61
   300.1 1008.32   310.1 1010.15     320 1017.19     330 1018.99     350 1031.83
   359.9 1036.48   369.9  1038.6   379.7 1039.28   409.2 1042.91   428.9 1046.61
   438.7  1049.2   448.5 1052.79   458.3 1056.96   468.2 1059.53     478 1060.85
#Mann= 3 , 0 , 0
      10     .06       0   290.1    .045       0   310.1     .08       0
Bank Sta=290.1,310.1
XS Rating Curve= 0 ,0
Exp/Cntr=0.3,0.1

Type RM Length L Ch R = 1 ,59875.8 ,29.9,33.8,38.4
XS GIS Cut Line= 6
     1637229.682      326333.129     1637185.018      326483.001
      1637232.66      326583.247     1637279.309      326637.837
     1637378.277      326787.329     1637364.667      326977.283
#Sta/Elev= 30
     9.8 1075.35    19.5 1072.21    29.3 1064.19    68.4 1027.52    78.2 1019.87
      88 1016.46   146.6 1016.19   166.5 1013.25   176.6 1012.57   294.3 1012.66
   339.2 1012.29   349.1  1011.7   369.1 1009.15     379 1008.58     389  1007.6
     399 1008.03   428.8 1009.97   478.6 1009.88   488.6 1011.18   508.5 1017.14
   518.5 1023.17   528.5 1025.66   538.5 1027.52   548.5  1028.5   558.6 1028.91
   588.6 1029.12   628.7 1026.86   648.8 1024.49   678.8    1020   708.9 1017.52
#Mann= 3 , 0 , 0
     9.8     .06       0     379    .045       0     399     .06       0
#XS Ineff= 2 , 0
       0     370    1012     412       0    1012
Permanent Ineff=
       F       F
Bank Sta=379,399
XS Rating Curve= 0 ,0
Exp/Cntr=0.3,0.1

Type RM Length L Ch R = 1 ,59842   ,142,162.6,183.3
XS GIS Cut Line= 6
     1637185.018      326319.234     1637140.149       326510.61
     1637212.809      326617.986     1637260.451       326658.68
     1637298.167       326741.06     1637310.387       326919.49
#Sta/Elev= 30
     9.8 1067.78    19.7    1061    29.5 1057.55    39.3 1049.06      59 1030.98
    68.8 1022.32    78.6 1016.77    88.5 1015.79   167.1 1014.91   176.9 1014.45
   196.6    1013   236.5 1011.66   256.4 1012.09   286.3 1011.51   344.1 1011.24
   379.9 1010.75   388.9 1010.24   398.9 1010.39   409.1 1008.46   419.1 1007.51
   429.1 1007.89   449.3 1009.79   469.4 1010.51   519.2 1010.96     559 1012.37
   568.9 1012.86   598.7 1016.16   608.6 1016.62   618.6 1016.62   658.3 1017.51
#Mann= 3 , 0 , 0
     9.8     .06       0   409.1    .045       0   429.1     .06       0
#XS Ineff= 2 , 0
       0     405    1011     442       0    1011
Permanent Ineff=
       F       F
Bank Sta=409.1,429.1
XS Rating Curve= 0 ,0
Exp/Cntr=0.3,0.1

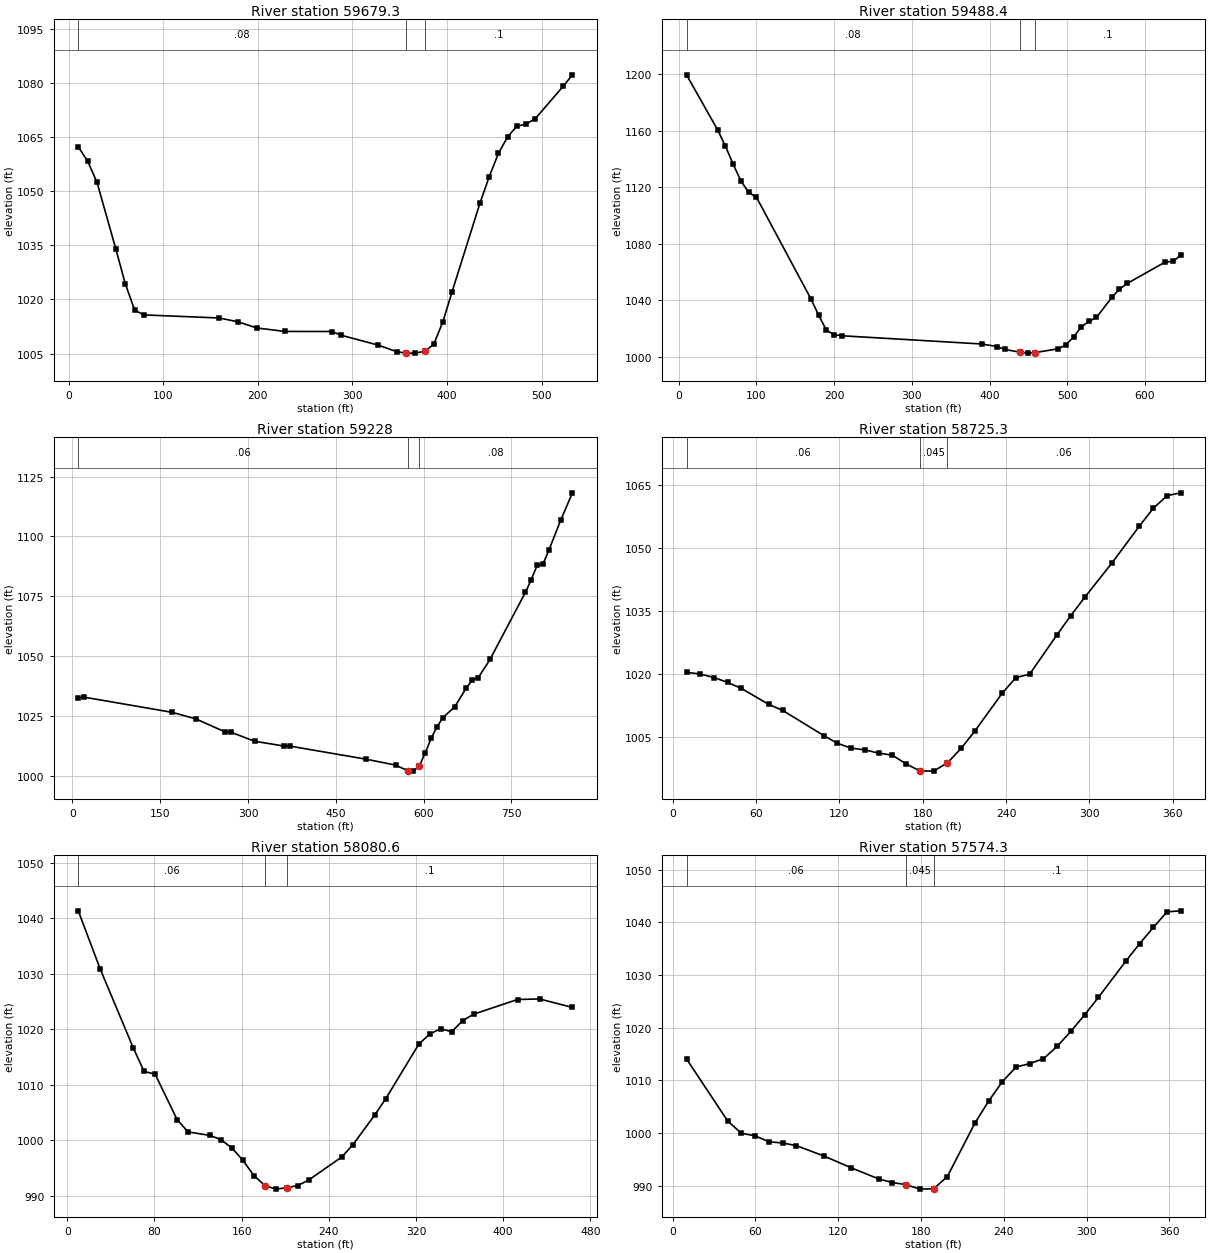
Type RM Length L Ch R = 1 ,59679.3 ,201.6,191,180.3
XS GIS Cut Line= 4
     1637176.206      326321.123     1637126.419      326513.523
     1637174.519      326576.812     1637031.062      326786.933
#Sta/Elev= 30
     9.9 1062.35    19.9 1058.34    29.8 1052.45    49.7 1033.95    59.6 1024.41
    69.6 1017.02    79.5 1015.71     159 1014.86   178.9  1013.8   198.7  1012.1
   228.5 1011.13   278.2 1011.11     288 1010.08   327.2 1007.33   346.7 1005.52
   356.3 1005.14   366.3 1005.11   376.3 1005.62   385.9 1007.51   395.7 1013.86
   405.4 1022.16   434.8 1046.67   444.6 1054.01   454.4 1060.53   464.2 1065.13
   473.9 1068.07   483.7 1068.64   493.5 1070.18   522.9 1079.14   532.7 1082.32
#Mann= 3 , 0 , 0
     9.9     .08       0   356.3    .045       0   376.3      .1       0
Bank Sta=356.3,376.3
XS Rating Curve= 0 ,0
Exp/Cntr=0.3,0.1

Type RM Length L Ch R = 1 ,59488.4 ,265.9,260.4,254.9
XS GIS Cut Line= 3
     1637175.692      326158.467     1636983.753      326474.999
     1636964.358      326750.279
#Sta/Elev= 30
      10 1199.32      50 1160.49      60 1149.07      70 1136.24      80 1124.42
      90 1116.34     100 1112.89   170.1 1041.14   180.1 1029.55   190.1 1018.92
   200.1 1015.82   210.1 1015.06   389.9 1009.26   409.6 1007.47   419.5 1005.41
     439 1003.51     449  1002.8     459 1003.22   488.4 1005.86   498.3 1008.61
   508.2  1014.2     518 1021.18   527.9  1025.2   537.7 1027.97   557.4 1042.12
   567.3    1048   577.2 1051.99   626.4 1067.19   636.3 1067.62   646.1 1071.92
#Mann= 3 , 0 , 0
      10     .08       0     439    .045       0     459      .1       0
Bank Sta=439,459
XS Rating Curve= 0 ,0
Exp/Cntr=0.3,0.1

Type RM Length L Ch R = 1 ,59228   ,506.3,502.7,499
XS GIS Cut Line= 3
     1636673.956      326023.773     1636701.474      326474.725
     1636781.712      326868.979
#Sta/Elev= 30
      10 1032.66    20.1 1032.96   170.7 1026.62   210.8  1023.9     261 1018.44
   271.1 1018.31   311.2 1014.57   361.4 1012.57   371.5 1012.55   502.1 1007.07
   552.4  1004.6   572.6 1002.29   582.6 1002.11   592.6 1004.27   602.7 1009.74
   612.7 1015.75   622.8 1020.65   632.8 1024.41     653 1028.92   673.1 1036.92
   683.1 1040.02   693.2 1041.09   713.3 1048.69   773.7 1076.65   783.7 1081.96
   793.8 1087.92   803.8 1088.52   813.9  1094.3     834 1106.73   854.1 1118.19
#Mann= 3 , 0 , 0
      10     .06       0   572.6    .045       0   592.6     .08       0
Bank Sta=572.6,592.6
XS Rating Curve= 0 ,0
Exp/Cntr=0.3,0.1

Type RM Length L Ch R = 1 ,58725.3 ,648.7,644.7,640.5
XS GIS Cut Line= 2
     1636205.474      326634.217     1636342.812      326973.203
#Sta/Elev= 30
     9.9 1020.38    19.8 1019.96    29.7 1019.13    39.5 1017.98    49.4 1016.54
    69.2 1012.73    79.1 1011.33   108.7 1005.34   118.6  1003.5   128.5 1002.35
   138.4 1001.94   148.3 1001.17   158.2 1000.67     168  998.61   177.8  996.96
   187.8  996.89   197.8  998.85   207.6 1002.27   217.5  1006.4   237.2 1015.38
   247.1 1019.12     257 1019.92   276.8 1029.33   286.7 1033.87   296.6 1038.16
   316.3 1046.36   336.1 1055.15     346 1059.33   355.9 1062.35   365.8 1063.03
#Mann= 3 , 0 , 0
     9.9     .06       0   177.8    .045       0   197.8     .06       0
Bank Sta=177.8,197.8
XS Rating Curve= 0 ,0
Exp/Cntr=0.3,0.1

Type RM Length L Ch R = 1 ,58080.6 ,486.4,506.2,519.5
XS GIS Cut Line= 2
     1635578.796       326824.03     1635839.815      327207.084
#Sta/Elev= 30
    10.1 1041.37    30.2 1030.89    60.5 1016.68    70.5 1012.39    80.6 1011.91
   100.8 1003.71   110.8 1001.48     131 1000.85   141.1 1000.08   151.2  998.56
   161.2  996.35   171.3  993.59   181.5  991.79   191.5  991.16   201.5  991.42
   211.6  991.81   221.7  992.83   251.9  996.96     262  999.15   282.1 1004.53
   292.2 1007.46   322.5  1017.3   332.5 1019.13   342.6 1020.11   352.7 1019.55
   362.8 1021.56   372.8 1022.72   413.1 1025.37   433.3 1025.47   463.5 1023.94
#Mann= 3 , 0 , 0
    10.1     .06       0   181.5    .045       0   201.5      .1       0
Bank Sta=181.5,201.5
XS Rating Curve= 0 ,0
Exp/Cntr=0.3,0.1

Type RM Length L Ch R = 1 ,57574.3 ,682.3,682.6,682.2
XS GIS Cut Line= 2
     1635337.106      326807.099     1635208.467      327152.251
#Sta/Elev= 30
      10 1014.07    39.8 1002.31    49.8  999.95    59.7  999.49    69.7  998.35
    79.6  998.12    89.6  997.62   109.5  995.66   129.4  993.41   149.3   991.3
   159.3  990.61   169.2  990.21   179.2  989.36   189.2  989.43   199.1  991.75
     219 1001.84     229 1006.06   238.9 1009.72   248.9 1012.54   258.8 1013.19
   268.8 1014.11   278.7 1016.46   288.7 1019.32   298.7 1022.46   308.6 1025.75
   328.5 1032.64   338.5 1035.95   348.4 1039.03   358.4    1042   368.3 1042.19
#Mann= 3 , 0 , 0
      10     .06       0   169.2    .045       0   189.2      .1       0
Bank Sta=169.2,189.2
XS Rating Curve= 0 ,0
Exp/Cntr=0.3,0.1

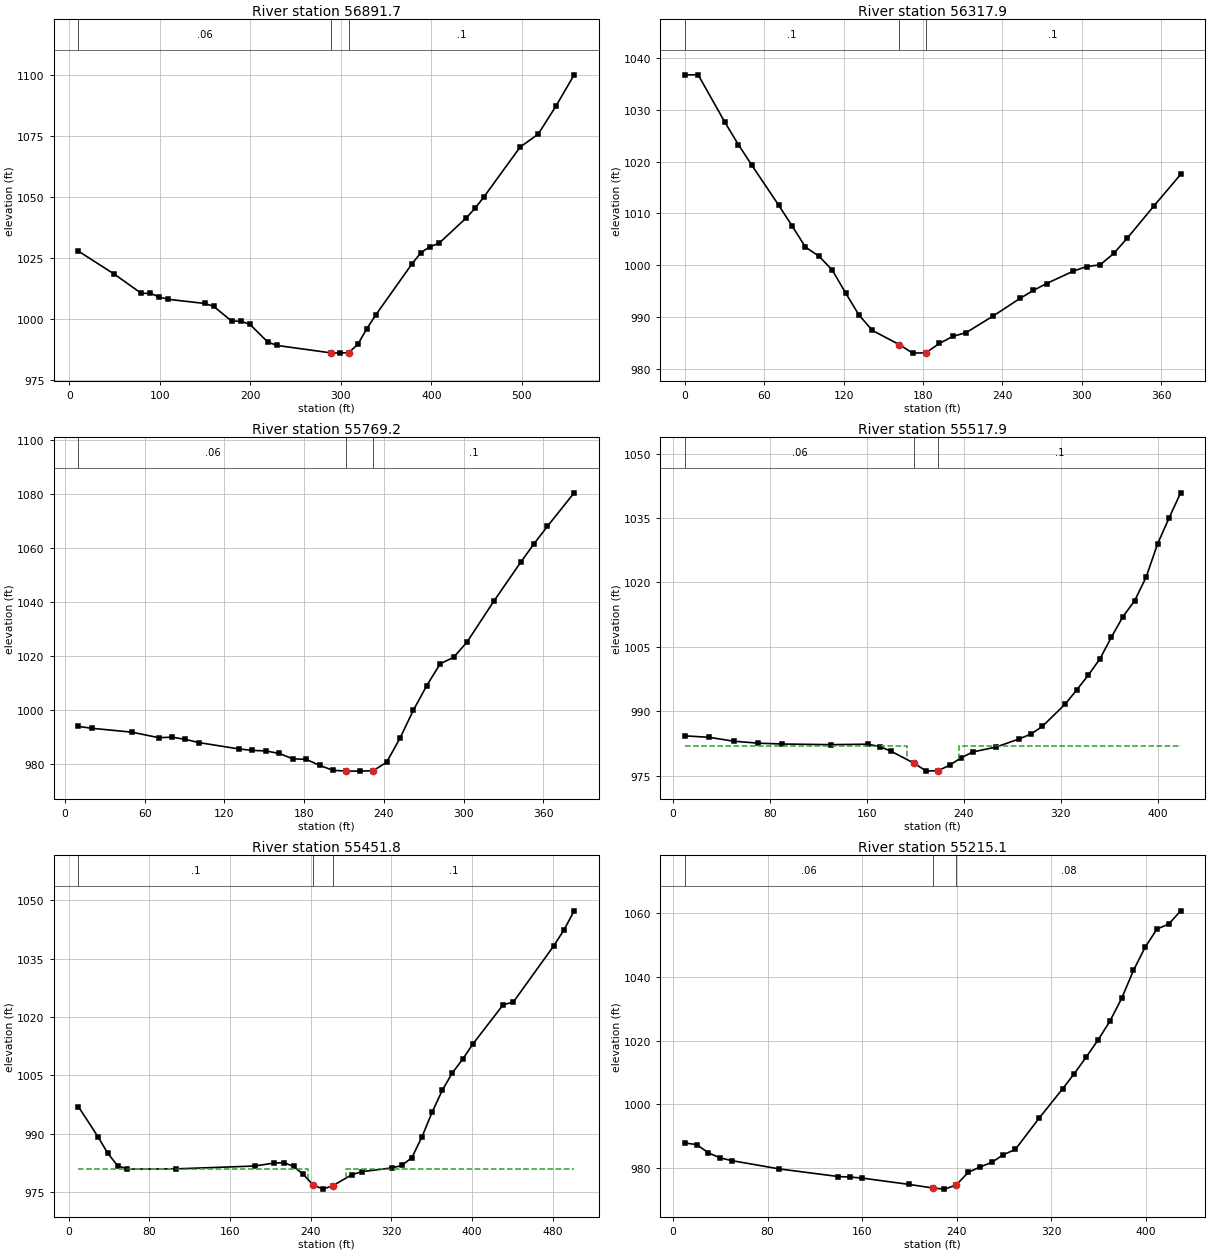
Type RM Length L Ch R = 1 ,56891.7 ,577.3,573.8,570.3
XS GIS Cut Line= 2
       1634741.5      326603.689     1634544.888      327125.728
#Sta/Elev= 30
      10 1027.85    49.8 1018.42    79.7 1010.56    89.7 1010.63    99.6 1009.04
   109.6 1008.13   149.4 1006.47   159.4  1005.3   179.3  999.27   189.3  999.18
   199.2  998.06   219.1  990.75   229.1  989.32   288.8  986.28   298.8  986.16
   308.8   986.4   318.8  989.75   328.7  996.14   338.7 1001.81   378.5 1022.57
   388.5 1027.18   398.5 1029.67   408.4 1031.01   438.3 1041.31   448.3 1045.32
   458.2 1050.02   498.1 1070.35     518 1075.61   537.9 1087.22   557.8 1099.87
#Mann= 3 , 0 , 0
      10     .06       0   288.8    .045       0   308.8      .1       0
Bank Sta=288.8,308.8
XS Rating Curve= 0 ,0
Exp/Cntr=0.3,0.1

Type RM Length L Ch R = 1 ,56317.9 ,555.8,548.7,541.6
XS GIS Cut Line= 2
     1634206.771      326423.269     1634134.664      326791.085
#Sta/Elev= 30
       0 1036.82    10.1 1036.82    30.4  1027.6    40.5 1023.32    50.7 1019.32
    70.9 1011.62      81 1007.64    91.2 1003.49   101.3 1001.76   111.4  999.08
   121.6   994.6   131.7  990.34   141.8  987.37   162.2  984.62   172.2  982.98
   182.2  983.04   192.5  984.86   202.6  986.22   212.7  986.95     233  990.15
   253.3  993.55   263.4   995.1   273.5  996.45   293.8  998.86   303.9  999.73
     314 1000.07   324.2 1002.26   334.3 1005.17   354.6 1011.45   374.8 1017.55
#Mann= 3 , 0 , 0
       0      .1       0   162.2    .045       0   182.2      .1       0
Bank Sta=162.2,182.2
XS Rating Curve= 0 ,0
Exp/Cntr=0.3,0.1

Type RM Length L Ch R = 1 ,55769.2 ,219.3,251.4,275.6
XS GIS Cut Line= 2
     1633642.469      326590.064     1633704.477      326968.113
#Sta/Elev= 30
    10.1  993.76    20.2  993.07    50.4  991.63    70.6  989.59    80.7  989.77
    90.7  988.95   100.8  987.77   131.1   985.4   141.1  984.88   151.2  984.67
   161.3  983.74   171.4  981.76   181.5  981.56   191.6  979.34   201.6  977.51
   211.8  977.21   221.8   977.2   231.8  977.34     242  980.46     252  989.33
   262.1  999.71   272.2 1008.87   282.3 1016.95   292.4 1019.34   302.4 1024.93
   322.6 1040.09   342.8  1054.5   352.9 1061.39   362.9 1067.82   383.1 1080.27
#Mann= 3 , 0 , 0
    10.1     .06       0   211.8    .045       0   231.8      .1       0
Bank Sta=211.8,231.8
XS Rating Curve= 0 ,0
Exp/Cntr=0.3,0.1

Type RM Length L Ch R = 1 ,55517.9 ,73.3,66.1,66.7
XS GIS Cut Line= 4
     1633530.513      326631.881     1633463.021      326788.701
     1633374.685      326846.268     1633401.484      326986.215
#Sta/Elev= 30
      10   984.3    30.1  983.96    50.2  983.06    70.3   982.6    90.4   982.4
   130.6  982.25   160.7  982.36   170.7  981.81   180.3  980.68   199.1  977.91
   209.1  976.09   219.1  976.23   228.2  977.46   237.8  979.19   247.4  980.55
   266.6   981.7   285.7  983.59   295.2   984.7   304.7  986.49   323.7  991.73
   333.2  995.04   342.7  998.47   352.2 1002.22   361.7  1007.3   371.2 1012.07
   380.7 1015.69   390.2 1021.19   399.7 1028.98   409.2 1035.02   418.7 1040.86
#Mann= 3 , 0 , 0
      10     .06       0   199.1    .045       0   219.1      .1       0
#XS Ineff= 2 , 0
       0     193     982     236       0     982
Permanent Ineff=
       F       F
Bank Sta=199.1,219.1
XS Rating Curve= 0 ,0
Exp/Cntr=0.3,0.1

Type RM Length L Ch R = 1 ,55451.8 ,269.9,236.7,203.6
XS GIS Cut Line= 4
     1633465.998      326567.367     1633433.245      326739.075
     1633320.096      326813.515     1633306.201      327004.081
#Sta/Elev= 30
     9.7     997    29.1  989.28    38.8  985.02    48.6  981.82    58.3  980.92
   106.8  980.99   184.5  981.72   203.8  982.48   213.5  982.59   223.2  981.61
   232.8  979.56   242.2  976.92   252.2  975.78   262.2  976.69   281.2  979.53
   290.9  980.27   320.3  981.23   330.4  981.86   340.4  983.88   350.5  989.27
   360.5  995.57   370.6 1001.21   380.6  1005.7   390.7 1009.15   400.8 1013.06
   430.9 1023.17     441 1023.87   481.2 1038.37   491.3 1042.45   501.3 1047.32
#Mann= 3 , 0 , 0
     9.7      .1       0   242.2    .045       0   262.2      .1       0
#XS Ineff= 2 , 0
       0     237     981     275       0     981
Permanent Ineff=
       F       F
Bank Sta=242.2,262.2
XS Rating Curve= 0 ,0
Exp/Cntr=0.3,0.1

Type RM Length L Ch R = 1 ,55215.1 ,309.8,316.7,323.6
XS GIS Cut Line= 2
     1633036.112        326681.7       1633273.7      327039.259
#Sta/Elev= 30
      10   987.9      20  987.41      30  984.82    39.9  983.23    49.9  982.37
    89.9  979.78   139.8   977.4   149.8  977.23   159.7  976.92   199.7  974.93
   219.6  973.81   229.6  973.45   239.6  974.74   249.6  978.68   259.6  980.38
   269.6  981.83   279.5  984.25   289.5  985.88   309.5  995.62   329.5 1004.88
   339.4 1009.66   349.4  1014.8   359.4 1020.14   369.4 1026.01   379.4 1033.18
   389.4 1041.96   399.3 1049.25   409.3 1054.95   419.3 1056.51   429.3 1060.65
#Mann= 3 , 0 , 0
      10     .06       0   219.6    .045       0   239.6     .08       0
Bank Sta=219.6,239.6
XS Rating Curve= 0 ,0
Exp/Cntr=0.3,0.1