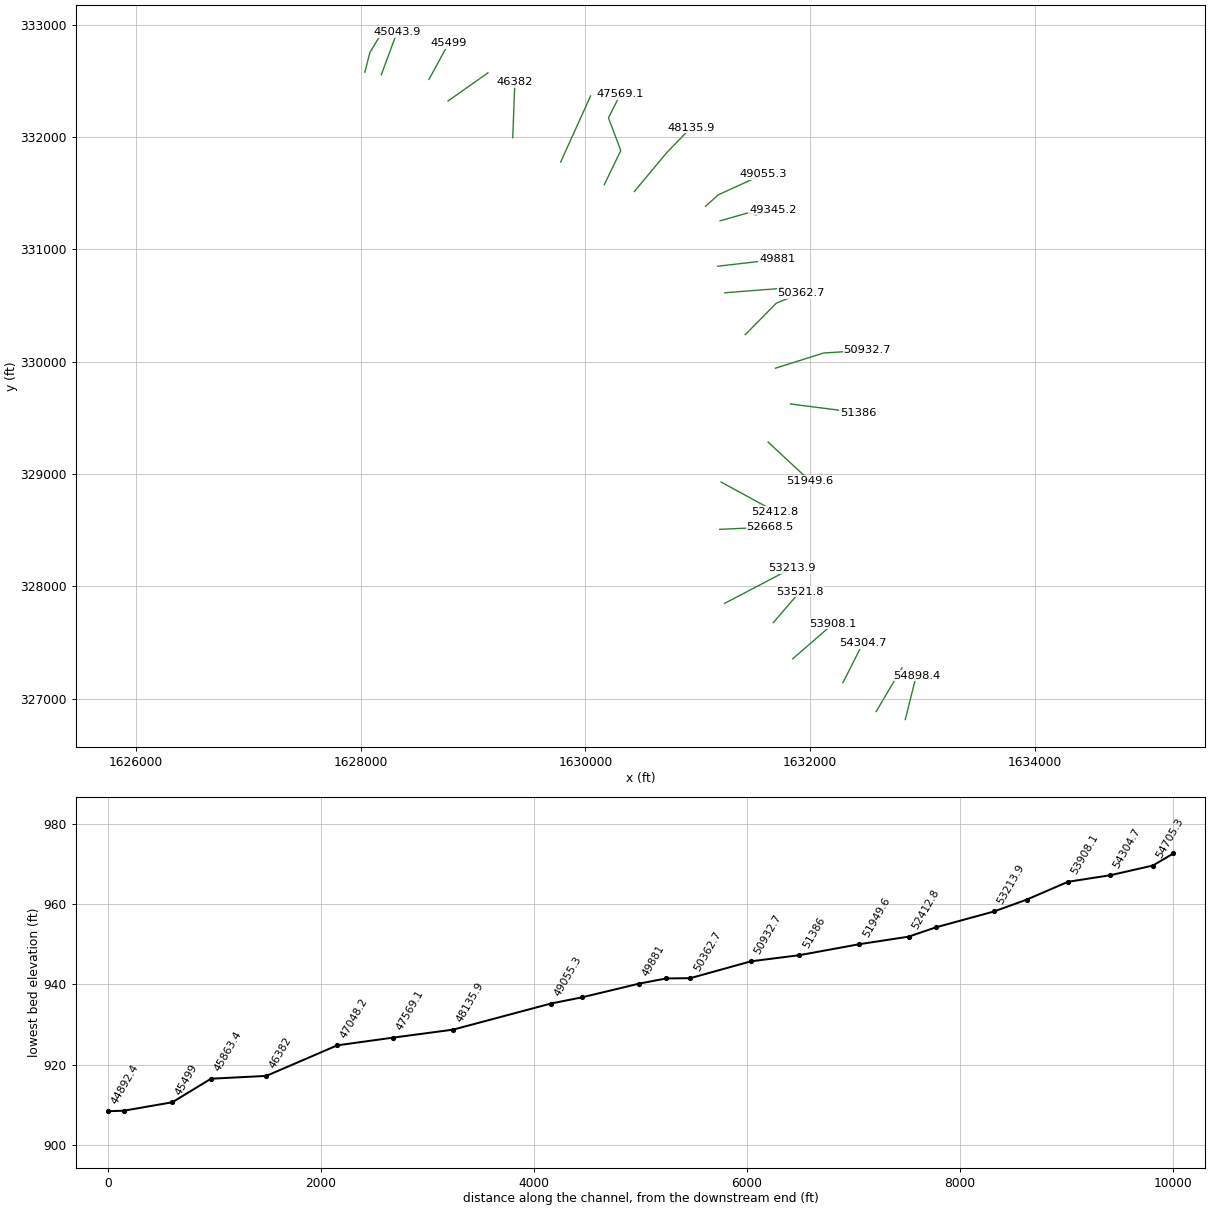
HEC-RAS study stfrktwl1.prj: stfrktwl1

--- stfrktwl1.g01 (geometry) --- (continued)

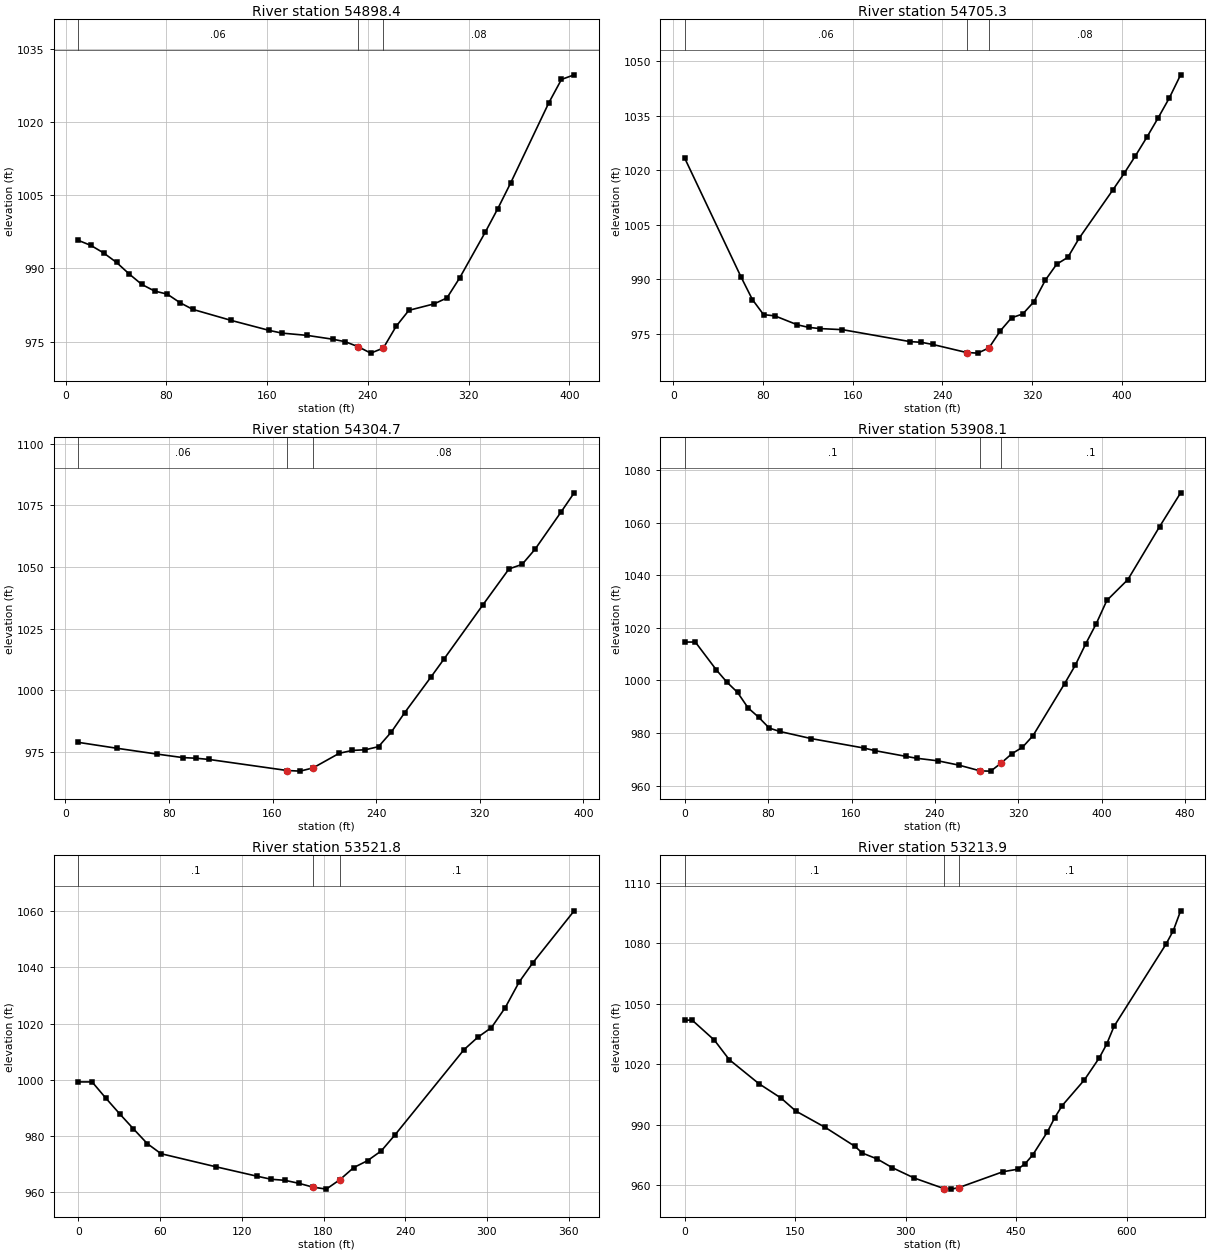
Type RM Length L Ch R = 1 ,54898.4 ,198.9,193.1,187.3
XS GIS Cut Line= 2
     1632849.099      326813.432     1632946.722        327205.1
#Sta/Elev= 30
    10.1  995.75    20.2   994.7    30.3  993.15    40.4  991.23    50.5  988.85
    60.5  986.71    70.6  985.36    80.7  984.72    90.8  982.97   100.9   981.6
   131.2  979.35   161.5  977.29   171.6  976.73   191.7  976.26   211.9  975.48
     222  974.96   232.2  973.94   242.2  972.62   252.2  973.65   262.4  978.13
   272.5   981.4   292.6  982.73   302.7  983.94   312.8  988.04     333  997.37
   343.1 1002.27   353.2 1007.48   383.5 1023.93   393.6 1028.76   403.7 1029.71
#Mann= 3 , 0 , 0
    10.1     .06       0   232.2    .045       0   252.2     .08       0
Bank Sta=232.2,252.2
XS Rating Curve= 0 ,0
Exp/Cntr=0.3,0.1

Type RM Length L Ch R = 1 ,54705.3 ,399.2,400.6,402
XS GIS Cut Line= 2
     1632589.163      326884.003     1632819.694      327273.319
#Sta/Elev= 30
    10.1 1023.25    60.3  990.56    70.4  984.36    80.4   980.2    90.5  979.86
   110.6  977.39   120.7  976.69   130.7  976.36   150.8  976.06   211.1  972.77
   221.2  972.58   231.3  971.99   261.5  969.77   271.5   969.6   281.5  971.05
   291.6  975.73   301.6  979.32   311.7   980.4   321.7  983.79   331.8   989.7
   341.9  994.09   351.9  995.99     362 1001.27   392.1 1014.57   402.2 1019.16
   412.2 1023.95   422.3 1029.03   432.3 1034.31   442.4 1039.87   452.5 1046.25
#Mann= 3 , 0 , 0
    10.1     .06       0   261.5    .045       0   281.5     .08       0
Bank Sta=261.5,281.5
XS Rating Curve= 0 ,0
Exp/Cntr=0.3,0.1

Type RM Length L Ch R = 1 ,54304.7 ,404.4,396.6,388.7
XS GIS Cut Line= 2
     1632294.334      327142.655     1632471.545      327493.264
#Sta/Elev= 23
    10.1  978.85    40.3  976.42    70.5  974.12    90.7  972.67   100.7  972.42
   110.8  971.93   171.3  967.43   181.3  967.18   191.3  968.49   211.5  974.42
   221.6  975.58   231.7  975.85   241.8  977.11   251.8  983.12   261.9  990.83
     282 1005.16   292.1 1012.48   322.3 1034.58   342.5  1049.2   352.6 1051.04
   362.6 1057.17   382.8 1072.38   392.8 1080.07
#Mann= 3 , 0 , 0
    10.1     .06       0   171.3    .045       0   191.3     .08       0
Bank Sta=171.3,191.3
XS Rating Curve= 0 ,0
Exp/Cntr=0.3,0.1

Type RM Length L Ch R = 1 ,53908.1 ,383.4,386.3,389.2
XS GIS Cut Line= 2
     1631846.993      327354.475     1632206.404      327666.321
#Sta/Elev= 30
       0  1014.6    10.1  1014.6    30.4 1003.95    40.5  999.32    50.6  995.47
    60.7  989.59    70.9  986.02      81  981.92    91.1  980.63   121.5   977.9
   172.1  974.31   182.2  973.35   212.6  971.13   222.7  970.43     243  969.46
   263.2  967.81   283.6  965.63   293.6  965.55   303.6  968.62   313.9  972.18
     324   974.6   334.1     979   364.5  998.82   374.6  1005.7   384.7  1013.9
   394.8 1021.55     405 1030.41   425.2 1038.35   455.6 1058.44   475.8  1071.3
#Mann= 3 , 0 , 0
       0      .1       0   283.6    .045       0   303.6      .1       0
Bank Sta=283.6,303.6
XS Rating Curve= 0 ,0
Exp/Cntr=0.3,0.1

Type RM Length L Ch R = 1 ,53521.8 ,315.7,308,300.2
XS GIS Cut Line= 2
     1631673.974      327676.607     1631911.268      327952.628
#Sta/Elev= 26
       0  999.26    10.1  999.26    20.2  993.48    30.3  987.93    40.4  982.59
    50.6  977.32    60.7  973.72   101.1  969.06   131.4  965.69   141.6  964.63
   151.7  964.25   161.8   963.2     172  961.86     182  961.12     192  964.47
   202.2   968.8   212.3  971.24   222.4  974.72   232.6   980.5   283.1 1010.72
   293.2 1015.13   303.3  1018.6   313.4 1025.69   323.6 1034.79   333.7 1041.67
     364 1060.13
#Mann= 3 , 0 , 0
       0      .1       0     172    .045       0     192      .1       0
Bank Sta=172,192
XS Rating Curve= 0 ,0
Exp/Cntr=0.3,0.1

Type RM Length L Ch R = 1 ,53213.9 ,553.9,545.3,536.7
XS GIS Cut Line= 2
     1631239.774      327847.768     1631836.389      328159.635
#Sta/Elev= 30
       0 1041.86      10 1041.86    40.2 1031.94    60.3 1022.32   100.5 1010.43
   130.6 1003.28   150.7  996.85   190.9  988.69   231.1  979.33   241.1  976.01
   261.2  973.11   281.3  968.86   311.5  963.65   351.7  958.46   361.7  958.16
   371.7  958.87   432.1  966.79   452.2  968.03   462.2  970.81   472.3  975.04
   492.3  986.51   502.4  993.63   512.4  999.54   542.6  1012.3   562.7 1023.14
   572.7 1029.91   582.8  1038.8   653.1 1079.37   663.2 1086.16   673.2 1096.02
#Mann= 3 , 0 , 0
       0      .1       0   351.7    .045       0   371.7      .1       0
Bank Sta=351.7,371.7
XS Rating Curve= 0 ,0
Exp/Cntr=0.3,0.1

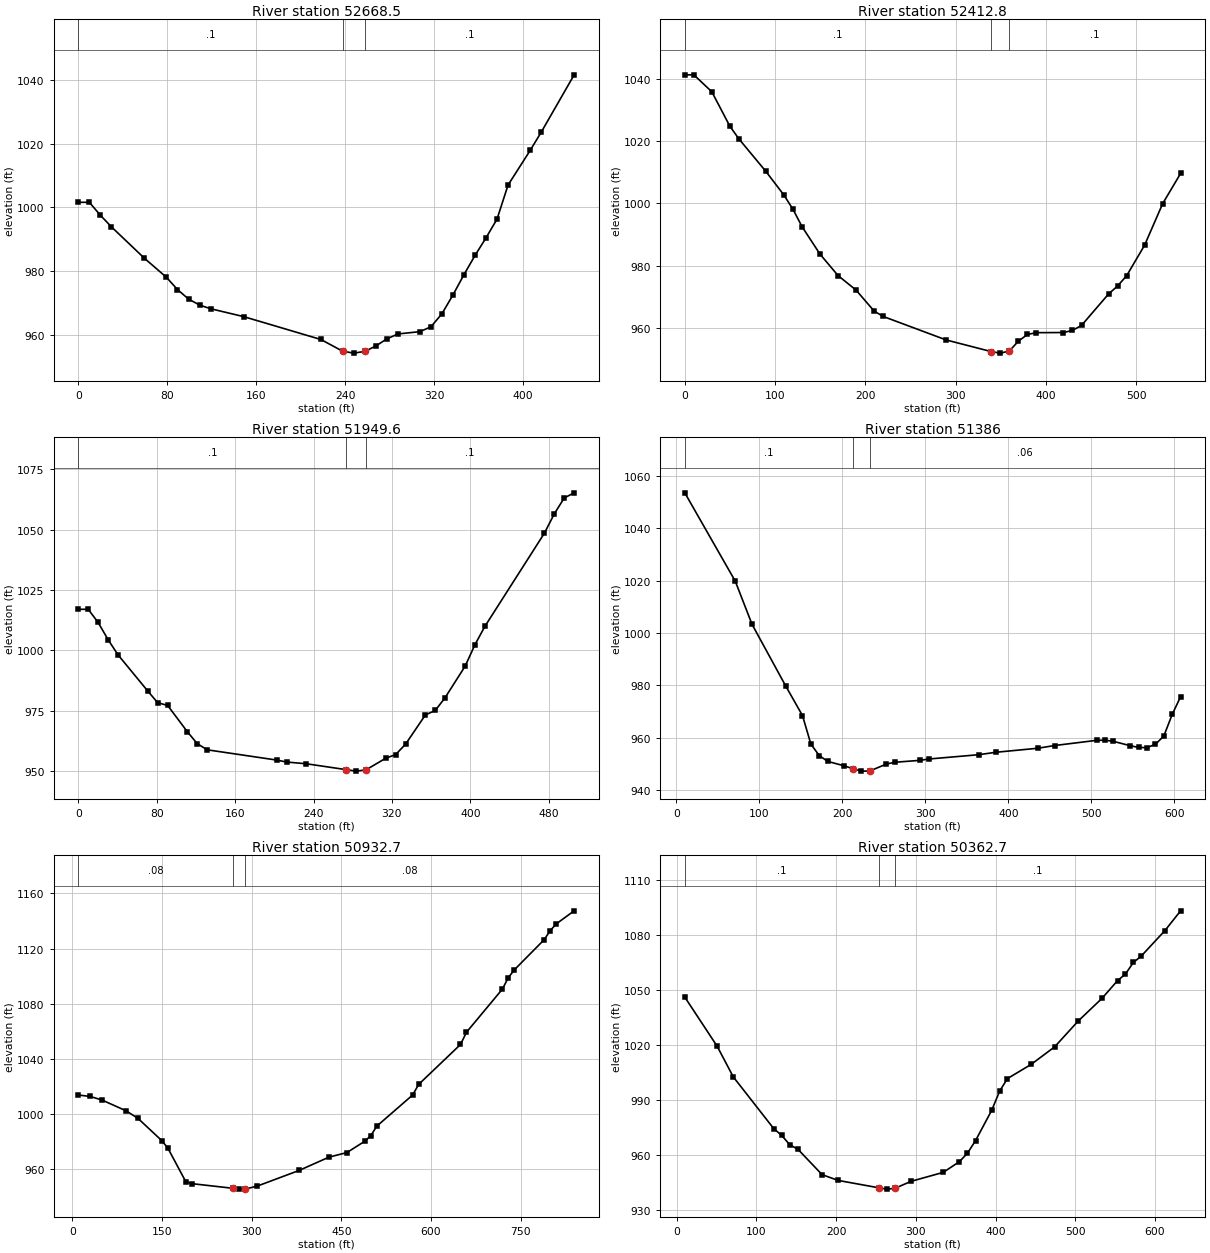
Type RM Length L Ch R = 1 ,52668.5 ,266.6,255.8,244.9
XS GIS Cut Line= 2
     1631196.565      328507.132     1631642.338      328527.127
#Sta/Elev= 30
       0 1001.56     9.9 1001.56    19.8  997.51    29.7  993.88    59.5  983.98
    79.3  978.01    89.2  974.17    99.2  971.18   109.1  969.31     119  968.15
   148.7  965.68   218.2   958.5   237.9  954.81   247.9  954.21   257.9  954.75
   267.7  956.45   277.6  958.67   287.6  960.23   307.4  960.95   317.3  962.48
   327.2  966.56   337.1  972.46   347.1  978.89     357  984.88   366.9  990.42
   376.8  996.29   386.7 1006.97   406.6 1017.84   416.5 1023.54   446.2 1041.58
#Mann= 3 , 0 , 0
       0      .1       0   237.9    .045       0   257.9      .1       0
Bank Sta=237.9,257.9
XS Rating Curve= 0 ,0
Exp/Cntr=0.3,0.1

Type RM Length L Ch R = 1 ,52412.8 ,468.2,463.2,458.2
XS GIS Cut Line= 2
     1631208.327      328928.205     1631690.561      328665.916
#Sta/Elev= 30
       0 1041.18      10 1041.18    29.9 1035.75    49.9 1024.68    59.9 1020.62
    89.8 1010.18   109.8 1002.58   119.8  998.01   129.8  992.46   149.7  983.64
   169.7  976.76   189.6  972.11   209.6  965.38   219.6  963.66   289.4  956.11
   339.3  952.38   349.3  951.89   359.3  952.56   369.3  955.73   379.3  957.88
   389.3  958.45   419.2   958.5   429.2  959.18   439.2  960.78   469.1  970.86
   479.1  973.43   489.1  976.71     509  986.51     529  999.84   548.9 1009.55
#Mann= 3 , 0 , 0
       0      .1       0   339.3    .045       0   359.3      .1       0
Bank Sta=339.3,359.3
XS Rating Curve= 0 ,0
Exp/Cntr=0.3,0.1

Type RM Length L Ch R = 1 ,51949.6 ,551,563.6,576.2
XS GIS Cut Line= 2
     1631627.047      329284.587     1631997.544      328939.966
#Sta/Elev= 30
       0 1016.99    10.1 1016.99    20.2 1011.53    30.4  1004.4    40.5  998.13
    70.8  983.19      81  978.32    91.1  977.21   111.3  966.29   121.4  961.36
   131.6  958.83   202.4  954.59   212.5  953.78   232.8  953.05   273.4  950.62
   283.4  950.01   293.4   950.5   313.7  955.34   323.8  956.85     334  961.19
   354.2  973.28   364.3  975.13   374.4  980.48   394.7  993.42   404.8 1002.38
   414.9 1009.92   475.6 1048.47   485.8 1056.54   495.9 1063.08     506 1065.19
#Mann= 3 , 0 , 0
       0      .1       0   273.4    .045       0   293.4      .1       0
Bank Sta=273.4,293.4
XS Rating Curve= 0 ,0
Exp/Cntr=0.3,0.1

Type RM Length L Ch R = 1 ,51386   ,444.5,453.3,462.2
XS GIS Cut Line= 2
     1631826.998      329623.327     1632429.615      329546.088
#Sta/Elev= 30
    10.1 1053.59    70.9 1019.84    91.1 1003.36   131.6  979.84   151.9  968.49
     162   957.6   172.1  953.21   182.3  950.99   202.5  949.26   212.8  948.17
   222.8  947.27   232.8  947.31   253.1  949.98   263.3  950.66   293.6  951.39
   303.8  951.89   364.5  953.55   384.8  954.47   435.4  956.01   455.7  957.05
   506.3  959.03   516.4  959.09   526.5  958.65   546.8  956.98   556.9  956.32
     567  956.25   577.2  957.53   587.3  960.71   597.4  968.97   607.5  975.72
#Mann= 3 , 0 , 0
    10.1      .1       0   212.8    .045       0   232.8     .06       0
Bank Sta=212.8,232.8
XS Rating Curve= 0 ,0
Exp/Cntr=0.3,0.1

Type RM Length L Ch R = 1 ,50932.7 ,560.2,570,579.8
XS GIS Cut Line= 3
     1631692.913      329942.072     1632121.453      330077.296
     1632510.972      330102.026
#Sta/Elev= 30
      10 1013.92      30 1012.87    49.9 1010.24    89.9 1002.48   109.8     997
   149.8  980.83   159.8  975.46   189.7  951.24   199.7  949.73   269.6  946.31
   279.6  945.75   289.6  945.83   309.6  947.98   379.5   959.3   429.4  968.92
   459.4  972.22   489.4  980.46   499.4  984.48   509.4  991.35   569.5 1013.96
   579.5 1021.62   649.5 1050.52   659.5 1059.39   719.6 1090.64   729.6 1099.03
   739.6 1104.61   789.6 1126.48   799.6 1132.97   809.6 1137.85   839.7 1147.35
#Mann= 3 , 0 , 0
      10     .08       0   269.6    .045       0   289.6     .08       0
Bank Sta=269.6,289.6
XS Rating Curve= 0 ,0
Exp/Cntr=0.3,0.1

Type RM Length L Ch R = 1 ,50362.7 ,241.3,227.1,212.9
XS GIS Cut Line= 3
     1631423.568      330240.822     1631701.452      330521.682
     1631921.136      330610.505
#Sta/Elev= 30
    10.1 1046.26    50.7 1019.46    70.9 1002.78   121.6  974.59   131.7  970.82
   141.8  965.75     152  963.29   182.4  949.42   202.6  946.29   253.4  942.28
   263.4  941.55   273.4  941.92   293.8  945.78   334.3  950.69   354.6  956.52
   364.7  961.16   374.8  967.98   395.1  984.54     405  994.93   414.8 1001.83
   444.5 1009.55   474.1 1019.16   503.7 1033.27   533.3 1045.52   553.1 1055.31
   562.9 1058.86   572.8 1065.15   582.7 1068.65   612.3 1082.51   632.1 1093.33
#Mann= 3 , 0 , 0
    10.1      .1       0   253.4    .045       0   273.4      .1       0
Bank Sta=253.4,273.4
XS Rating Curve= 0 ,0
Exp/Cntr=0.3,0.1

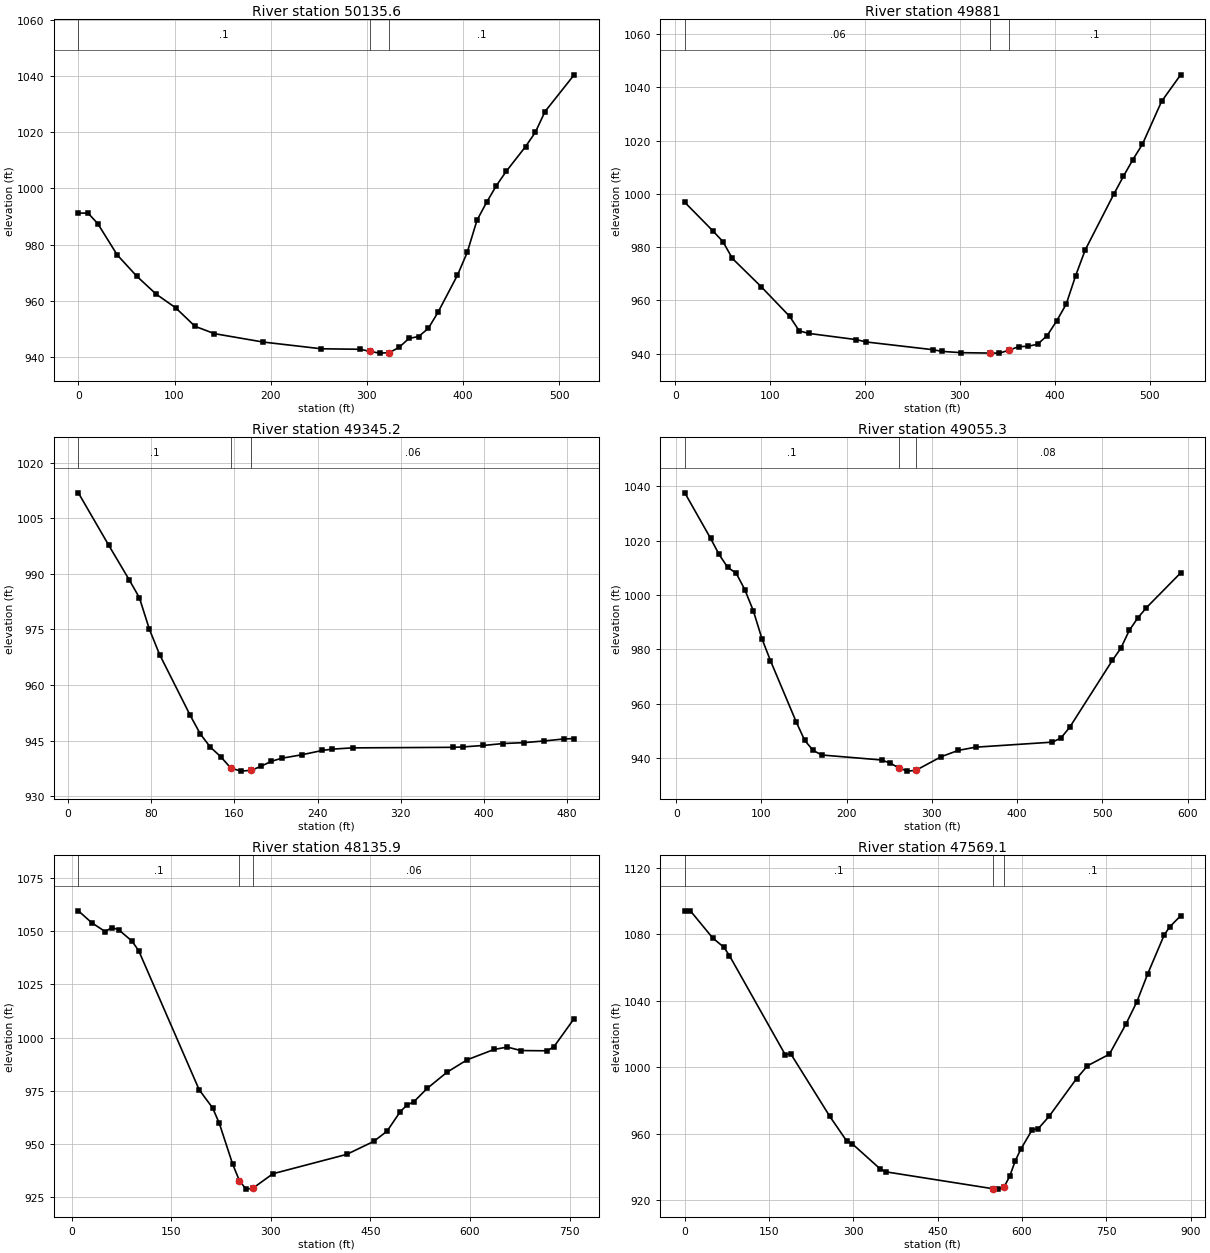
Type RM Length L Ch R = 1 ,50135.6 ,253.8,254.6,255.3
XS GIS Cut Line= 2
     1631242.436      330613.671     1631756.427      330653.662
#Sta/Elev= 30
       0  991.23    10.1  991.23    20.2  987.49    40.4  976.39    60.7  968.83
    80.9  962.44   101.1  957.61   121.3  951.01   141.5   948.4   192.1  945.42
   252.7  943.02   293.2  942.85   303.4  942.07   313.4  941.48   323.4  941.65
   333.6  943.56   343.7   946.7   353.8  947.38   363.9  950.29     374  956.03
   394.2  969.19   404.3  977.25   414.5  988.71   424.6  995.15   434.7 1001.02
   444.8 1006.04     465 1014.87   475.1 1019.92   485.2 1027.31   515.5 1040.36
#Mann= 3 , 0 , 0
       0      .1       0   303.4    .045       0   323.4      .1       0
Bank Sta=303.4,323.4
XS Rating Curve= 0 ,0
Exp/Cntr=0.3,0.1

Type RM Length L Ch R = 1 ,49881   ,532.8,535.8,538.9
XS GIS Cut Line= 2
     1631179.061      330850.145     1631708.342      330911.307
#Sta/Elev= 30
    10.1   996.8    40.2  985.91    50.3  982.04    60.3  975.72    90.5  965.17
   120.6     954   130.7  948.55   140.7  947.58     191  945.25   201.1  944.38
   271.4  941.48   281.5  940.82   301.6  940.35   331.8   940.2   341.8  940.18
   351.8  941.27   361.9  942.59     372  942.76     382  943.51   392.1  946.78
   402.1  952.24   412.2  958.58   422.2  969.33   432.3  978.99   462.4   999.9
   472.5 1006.59   482.5 1012.87   492.6 1018.67   512.7 1034.69   532.8 1044.69
#Mann= 3 , 0 , 0
    10.1     .06       0   331.8    .045       0   351.8      .1       0
Bank Sta=331.8,351.8
XS Rating Curve= 0 ,0
Exp/Cntr=0.3,0.1

Type RM Length L Ch R = 1 ,49345.2 ,287.4,289.9,292.4
XS GIS Cut Line= 4
     1631200.094       331254.69     1631444.739      331324.085
     1631520.015      331307.618     1631668.213      331354.665
#Sta/Elev= 29
     9.8 1011.84    39.1  997.67    58.7  988.39    68.5  983.57    78.2     975
      88  968.21   117.4  951.83   127.1  946.81   136.9  943.21   146.7  940.69
   156.3  937.65   156.5  937.58   166.3  936.77   176.3     937   185.8  938.12
   195.6  939.43   205.4  940.24     225  941.19   244.5  942.35   254.3  942.71
   273.6  943.04   370.2  943.19   379.9   943.3   399.4  943.69   418.8  944.22
   438.3  944.45   457.7   944.9   477.1  945.45   486.8  945.56
#Mann= 3 , 0 , 0
     9.8      .1       0   156.3    .045       0   176.3     .06       0
Bank Sta=156.3,176.3
XS Rating Curve= 0 ,0
Exp/Cntr=0.3,0.1

Type RM Length L Ch R = 1 ,49055.3 ,909.4,919.4,929
XS GIS Cut Line= 3
     1631070.714       331384.07     1631182.455      331485.212
     1631583.528      331668.705
#Sta/Elev= 30
      10 1037.65    40.2 1020.93    50.2 1014.97    60.3 1010.23    70.3 1008.08
    80.4 1002.03    90.4  994.26   100.5  983.98   110.5   975.9   140.7  953.38
   150.7  946.54   160.7  942.84   170.8  941.17   240.9  939.34     251  938.19
     261  936.45     271  935.24     281  935.51   311.1  940.58   331.1  942.89
   351.2  944.05   441.4  945.91   451.4  947.45   461.5  951.31   511.6  975.95
   521.6  980.45   531.6  987.06   541.7  991.67   551.7   995.4   591.8 1008.17
#Mann= 3 , 0 , 0
      10      .1       0     261    .045       0     281     .08       0
Bank Sta=261,281
XS Rating Curve= 0 ,0
Exp/Cntr=0.3,0.1

Type RM Length L Ch R = 1 ,48135.9 ,545.5,566.8,588.2
XS GIS Cut Line= 3
     1630436.377      331515.598     1630727.905      331864.753
     1630938.076      332081.704
#Sta/Elev= 30
    10.1 1059.63    30.3 1054.02    50.5 1049.88    60.6 1051.75    70.8 1050.76
      91 1045.36   101.1 1040.81   192.1  975.47   212.3  966.96   222.4  959.71
   242.6  940.42   252.8  932.64   262.8  928.73   272.8  929.12   303.2  935.97
   414.4  945.08   454.9  951.16     475  955.96   495.1  965.22   505.2  968.29
   515.3  969.77   535.4  976.08   565.6  983.76   595.8  989.57   636.1  994.41
   656.2  995.55   676.4  993.91   716.6  993.79   726.7   995.8   756.9 1008.97
#Mann= 3 , 0 , 0
    10.1      .1       0   252.8    .045       0   272.8     .06       0
Bank Sta=252.8,272.8
XS Rating Curve= 0 ,0
Exp/Cntr=0.3,0.1

Type RM Length L Ch R = 1 ,47569.1 ,536.4,520.9,505.4
XS GIS Cut Line= 4
     1630168.578      331576.615     1630315.606      331880.418
      1630205.87      332171.122     1630310.952      332380.012
#Sta/Elev= 30
       0  1094.2     9.9  1094.2    49.6 1077.88    69.5 1072.29    79.4 1067.25
   178.7  1007.6   188.6  1008.1   258.1  970.44   287.9  955.75   297.8  954.04
   347.5  938.92   357.6  937.14     548  926.98     558  926.73     568  927.97
   578.1  934.56   588.1  943.91   598.1  950.96   618.2  962.57   628.2  962.85
   648.2  970.57     697  993.25   716.4 1000.96   755.4 1007.93   784.6 1025.91
   804.1 1039.34   823.6 1056.32   852.8 1079.61   862.6 1084.53   882.1 1091.19
#Mann= 3 , 0 , 0
       0      .1       0     548    .045       0     568      .1       0
Bank Sta=548,568
XS Rating Curve= 0 ,0
Exp/Cntr=0.3,0.1

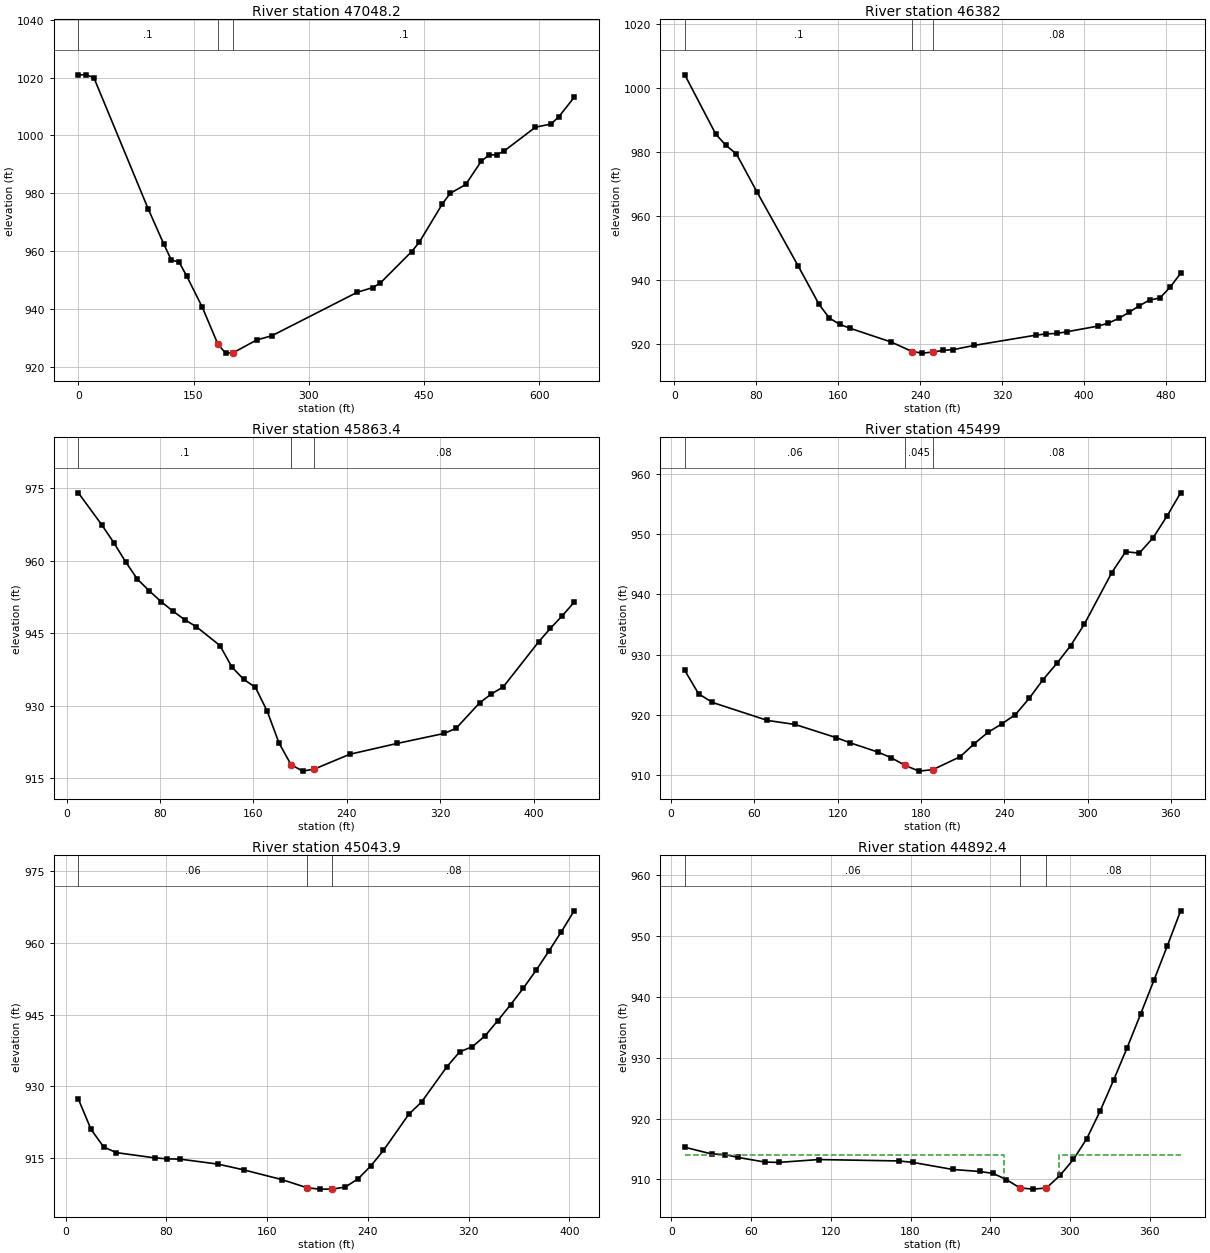
Type RM Length L Ch R = 1 ,47048.2 ,658.7,666.2,673.6
XS GIS Cut Line= 2
     1629780.444       331778.09     1630046.543      332366.453
#Sta/Elev= 30
       0 1020.95    10.1 1020.95    20.2 1019.98    90.8  974.75     111  962.66
   121.1  956.97   131.2  956.29   141.3  951.35   161.4   940.7   181.7  927.94
   191.7  924.82   201.7  924.96   232.1  929.34   252.2  930.84   363.2  945.84
   383.4  947.46   393.5  949.09   433.9  959.85   443.9  963.07   474.2  976.43
   484.3  980.01   504.5  983.07   524.7   991.1   534.8  993.25   544.8  993.33
   554.9  994.71   595.3 1002.87   615.5 1003.95   625.6 1006.43   645.7 1013.17
#Mann= 3 , 0 , 0
       0      .1       0   181.7    .045       0   201.7      .1       0
Bank Sta=181.7,201.7
XS Rating Curve= 0 ,0
Exp/Cntr=0.3,0.1

Type RM Length L Ch R = 1 ,46382   ,537.1,518.6,500.2
XS GIS Cut Line= 2
      1629353.49      331994.507     1629372.309      332488.503
#Sta/Elev= 30
    10.1 1004.17    40.4  985.61    50.4   982.1    60.5  979.46    80.7  967.51
   121.1   944.3   141.2  932.46   151.3  928.16   161.4  926.21   171.5  924.98
   211.9  920.66   232.1  917.71   242.1  917.21   252.1  917.53   262.3  918.06
   272.4  918.31   292.6  919.61   353.1  922.83   363.2  923.22   373.3  923.36
   383.4  923.89   413.6  925.65   423.7  926.57   433.8  928.04   443.9  929.93
     454  932.02   464.1   933.8   474.2  934.44   484.3  937.87   494.4  942.15
#Mann= 3 , 0 , 0
    10.1      .1       0   232.1    .045       0   252.1     .08       0
Bank Sta=232.1,252.1
XS Rating Curve= 0 ,0
Exp/Cntr=0.3,0.1

Type RM Length L Ch R = 1 ,45863.4 ,355.1,364.3,373.6
XS GIS Cut Line= 2
     1628777.162      332321.486     1629132.368      332572.012
#Sta/Elev= 30
    10.1  974.06    30.3   967.4    40.4  963.78    50.5  959.83    60.7  956.19
    70.8   953.8    80.9  951.58      91  949.61   101.1  947.84   111.2  946.36
   131.4  942.47   141.5  938.07   151.6  935.51   161.7  933.84   171.8  928.93
     182  922.29   192.2  917.87   202.2  916.51   212.2  916.94   242.6     920
     283  922.23   323.5  924.31   333.6  925.36   353.8  930.64   363.9  932.48
     374  933.93   404.3  943.25   414.4  946.05   424.6  948.65   434.7  951.45
#Mann= 3 , 0 , 0
    10.1      .1       0   192.2    .045       0   212.2     .08       0
Bank Sta=192.2,212.2
XS Rating Curve= 0 ,0
Exp/Cntr=0.3,0.1

Type RM Length L Ch R = 1 ,45499   ,452.2,455.2,458.1
XS GIS Cut Line= 2
     1628606.961      332513.425     1628783.043      332835.476
#Sta/Elev= 28
     9.9  927.36    19.8  923.49    29.8  922.05    69.4  919.06    89.3  918.39
     119   916.2     129  915.34   148.8  913.82   158.7  912.85   168.6  911.59
   178.6  910.64   188.6  910.89   208.3  913.04   218.2  915.16   228.2  917.07
   238.1  918.47     248  920.03   257.9  922.71   267.8   925.8   277.8  928.52
   287.7  931.45   297.6  935.02   317.4   943.6   327.4  947.07   337.3  946.85
   347.2  949.41   357.1  952.96     367  956.86
#Mann= 3 , 0 , 0
     9.9     .06       0   168.6    .045       0   188.6     .08       0
Bank Sta=168.6,188.6
XS Rating Curve= 0 ,0
Exp/Cntr=0.3,0.1

Type RM Length L Ch R = 1 ,45043.9 ,155.2,151.4,147.7
XS GIS Cut Line= 2
     1628183.191      332555.545     1628323.156      332934.276
#Sta/Elev= 30
    10.1  927.37    20.2  921.01    30.3  917.32    40.4  916.16    70.7  915.07
    80.8  914.86    90.8  914.81   121.1  913.76   141.3  912.57   171.6  910.54
   191.9  908.81   201.9  908.54   211.9  908.55   222.1  908.98   232.2  910.69
   242.3  913.37   252.4  916.64   272.5  924.18   282.6  926.73   302.8  934.12
   312.9  937.22     323  938.29   333.1  940.56   343.2  943.75   353.3  947.05
   363.4   950.5   373.5  954.22   383.6   958.2   393.7  962.33   403.8  966.67
#Mann= 3 , 0 , 0
    10.1     .06       0   191.9    .045       0   211.9     .08       0
Bank Sta=191.9,211.9
XS Rating Curve= 0 ,0
Exp/Cntr=0.3,0.1

Type RM Length L Ch R = 1 ,44892.4 ,51.8,51.5,51.2
XS GIS Cut Line= 3
     1628036.226      332577.849     1628081.427      332753.617
     1628185.419      332926.627
#Sta/Elev= 26
    10.1  915.29    30.2  914.19    40.3  914.09    50.4  913.61    70.6  912.85
    80.7   912.8   110.9  913.27   171.4  913.04   181.5  912.81   211.8  911.64
     232  911.31     242     911   252.1  909.99   262.3  908.61   272.3  908.41
   282.3   908.6   292.5  910.66   302.6  913.29   312.7  916.71   322.8  921.29
   332.9  926.34     343  931.62   353.1  937.12   363.2  942.72   373.3  948.38
   383.3  954.13
#Mann= 3 , 0 , 0
    10.1     .06       0   262.3    .045       0   282.3     .08       0
#XS Ineff= 2 , 0
       0     250     914     292       0     914
Permanent Ineff=
       F       F
Bank Sta=262.3,282.3
XS Rating Curve= 0 ,0
Exp/Cntr=0.3,0.1