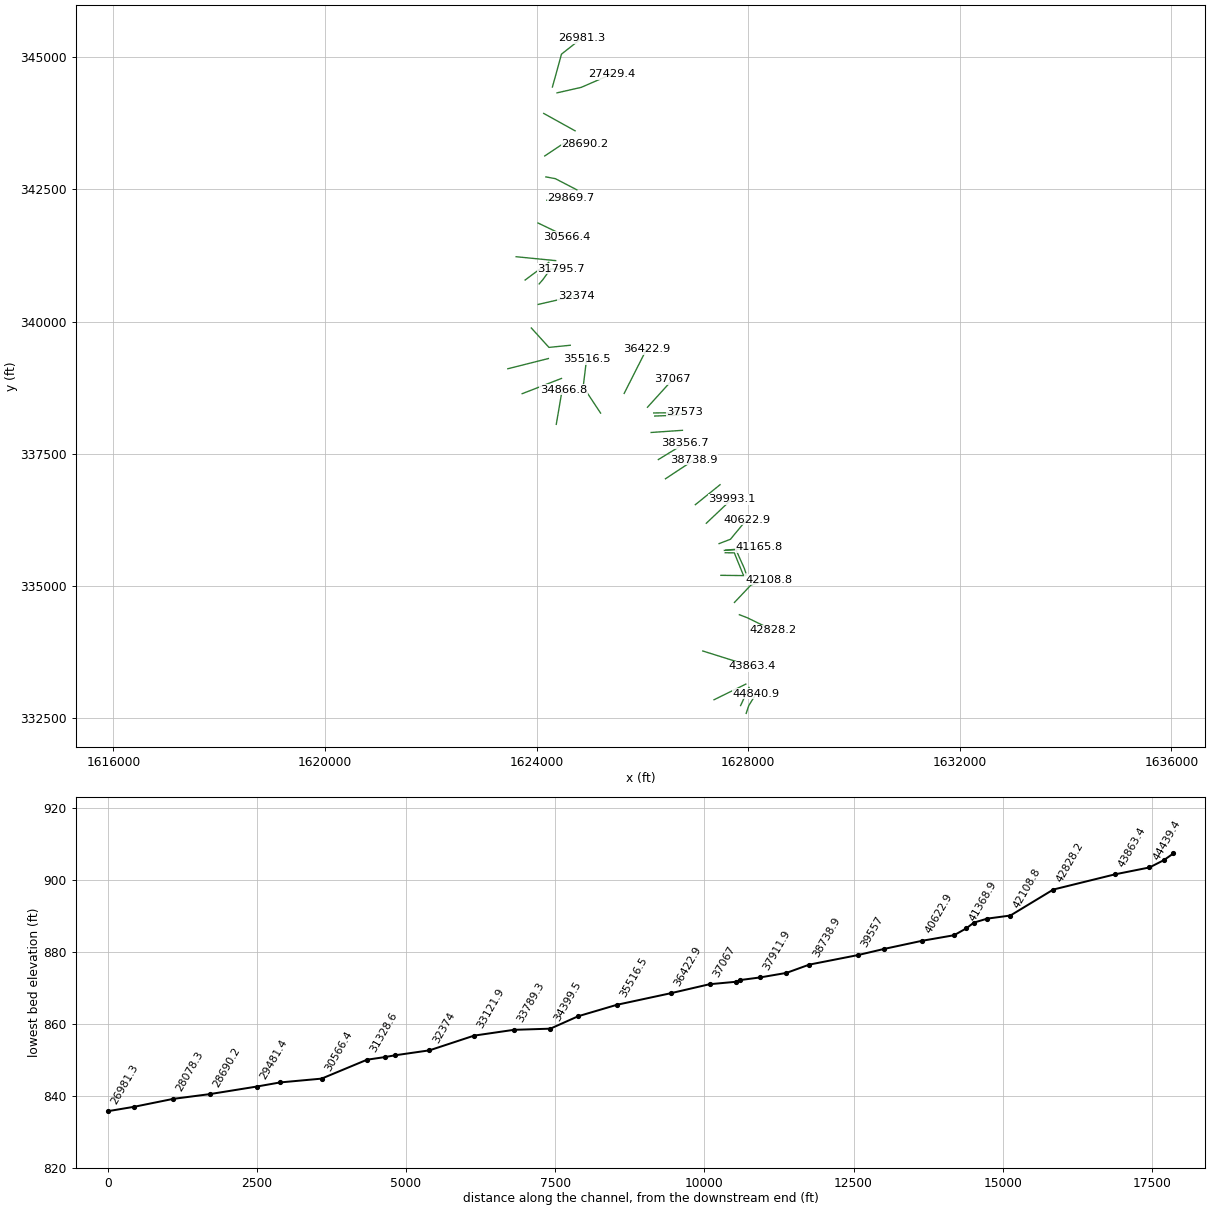
HEC-RAS study stfrktwl1.prj: stfrktwl1

--- stfrktwl1.g01 (geometry) --- (continued)

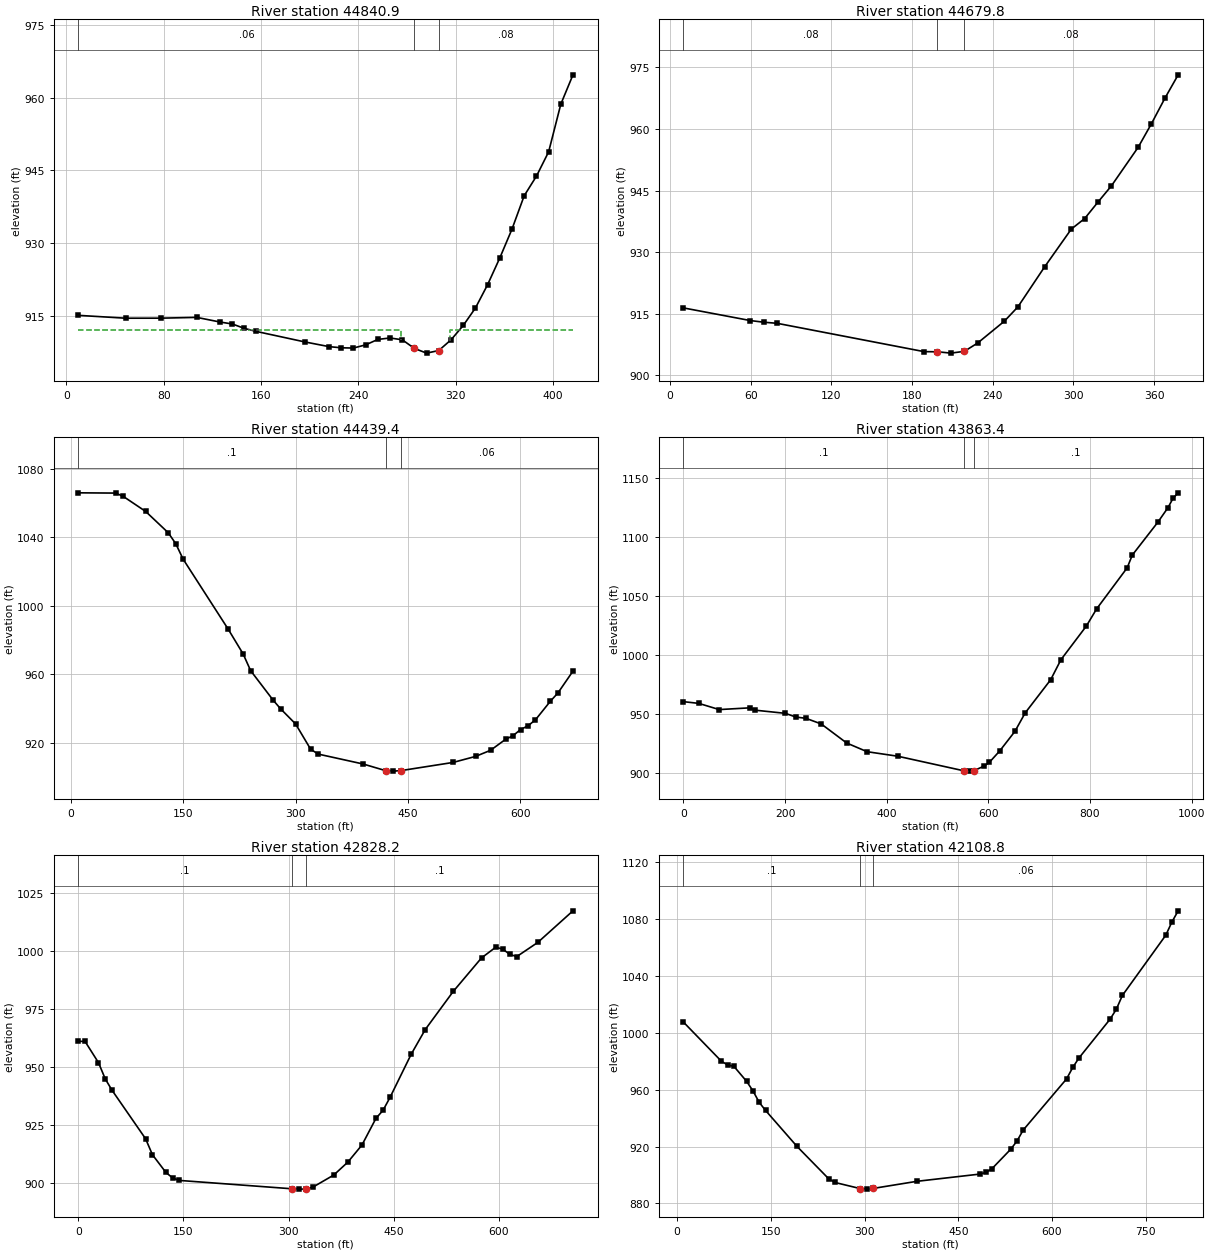
Type RM Length L Ch R = 1 ,44840.9 ,158.5,161.1,163.7
XS GIS Cut Line= 3
     1627962.332      332593.552     1628011.646      332741.268
     1628149.506       332962.54
#Sta/Elev= 30
     9.7  915.09    48.7   914.5    77.9  914.51   107.1  914.67   126.5   913.7
   136.3  913.31     146  912.42   155.7  911.79   195.8  909.61   215.9  908.63
   225.9  908.39   235.9  908.34     246     909     256  910.12     266  910.42
   276.1  910.04   286.1  908.25   296.1  907.29   306.1  907.83   316.2  910.05
   326.2     913   336.2   916.6   346.2  921.41   356.3  926.97   366.3  932.91
   376.3  939.78   386.4  943.84   396.4  948.85   406.4  958.68   416.4  964.75
#Mann= 3 , 0 , 0
     9.7     .06       0   286.1    .045       0   306.1     .08       0
#XS Ineff= 2 , 0
       0     275     912     315       0     912
Permanent Ineff=
       F       F
Bank Sta=286.1,306.1
XS Rating Curve= 0 ,0
Exp/Cntr=0.3,0.1

Type RM Length L Ch R = 1 ,44679.8 ,254.1,240.4,226.8
XS GIS Cut Line= 2
     1627857.097      332741.429     1628015.836      333084.529
#Sta/Elev= 20
     9.9  916.42    59.7  913.34    69.6  912.94    79.6  912.67     189  905.77
   198.9  905.74   208.9  905.41   218.9  905.85   228.8  907.87   248.7   913.2
   258.7  916.66   278.6  926.41   298.5  935.63   308.4  938.18   318.4  942.23
   328.3  946.14   348.2  955.53   358.1  961.28   368.1  967.48     378  973.19
#Mann= 3 , 0 , 0
     9.9     .08       0   198.9    .045       0   218.9     .08       0
Bank Sta=198.9,218.9
XS Rating Curve= 0 ,0
Exp/Cntr=0.3,0.1

Type RM Length L Ch R = 1 ,44439.4 ,591.4,576,560.6
XS GIS Cut Line= 2
     1627354.994      332851.203     1627956.188      333147.164
#Sta/Elev= 30
      10 1065.96      60 1065.81      70 1063.88     100 1055.06     130 1042.66
     140  1036.3     150 1027.15     210  986.34     230  971.83     240  962.08
     270  944.86     280  939.78     300  930.94     320  916.23     330  913.36
   390.1  907.55   420.1  903.67   430.1  903.39   440.1  903.66   510.1  908.46
   540.1  911.98   560.1  915.55   580.1  921.94   590.1  924.07   600.1  927.67
   610.1  929.85   620.1  933.39   640.1  944.29   650.1  949.09   670.1  961.81
#Mann= 3 , 0 , 0
      10      .1       0   420.1    .045       0   440.1     .06       0
Bank Sta=420.1,440.1
XS Rating Curve= 0 ,0
Exp/Cntr=0.3,0.1

Type RM Length L Ch R = 1 ,43863.4 ,1037.8,1035.2,1032.3
XS GIS Cut Line= 2
     1627141.432      333773.245     1628070.254      333481.717
#Sta/Elev= 30
       0  960.37    30.1  958.92    70.3  953.66   130.5  955.14   140.5  953.18
   200.7  950.46   220.8  947.36   240.9  946.26     271  941.49   321.2  925.31
   361.3  917.95   421.5  914.13     552  901.73     562  901.48     572  901.99
   592.1  905.86   602.2  909.05   622.2  918.54   652.3  935.22   672.4  950.83
   722.6  978.97   742.7   995.9   792.8 1024.48   812.9 1038.96   873.1 1073.83
   883.2 1084.64   933.4 1112.48   953.4 1124.83   963.5 1132.88   973.5 1137.43
#Mann= 3 , 0 , 0
       0      .1       0     552    .045       0     572      .1       0
Bank Sta=552,572
XS Rating Curve= 0 ,0
Exp/Cntr=0.3,0.1

Type RM Length L Ch R = 1 ,42828.2 ,694.4,719.5,744.6
XS GIS Cut Line= 3
     1627833.277        334458.9     1627977.065      334404.207
     1628473.648      334163.079
#Sta/Elev= 30
       0  961.07     9.6  961.07    28.8  951.89    38.5  944.85    48.1  939.98
    96.1  918.98   105.8  912.12     125  904.48   134.6  902.08   144.2  901.01
   304.4  897.41   314.4  897.25   324.4  897.26   334.5  898.06   364.6  903.34
   384.7  908.93   404.8   916.3   424.8  927.82   434.9  931.29   444.9  936.89
     475  955.47   495.1  966.16   535.2  982.68   575.4   997.1   595.5 1001.68
   605.5 1000.96   615.5  998.69   625.6  997.66   655.7 1003.79   705.9 1017.44
#Mann= 3 , 0 , 0
       0      .1       0   304.4    .045       0   324.4      .1       0
Bank Sta=304.4,324.4
XS Rating Curve= 0 ,0
Exp/Cntr=0.3,0.1

Type RM Length L Ch R = 1 ,42108.8 ,403.7,387.3,370.9
XS GIS Cut Line= 3
     1627740.653      334690.901     1628053.209      335020.984
     1628385.511      335122.409
#Sta/Elev= 30
    10.1 1007.46    70.7  980.03    80.8  977.36    90.9  976.34   111.1  965.86
   121.2  959.22   131.3  951.06   141.4  945.41   191.9  920.03   242.4  897.37
   252.5  894.72   293.1   890.4   303.1  890.03   313.1  890.48   383.9  895.53
   484.4   900.6   494.3  901.78   504.2  904.53     534  918.11   543.9  923.81
   553.9  931.57   623.3  967.53   633.3  975.64   643.2  982.28   692.8 1009.45
   702.8 1016.37   712.7 1026.26   782.2 1068.63   792.1 1078.04     802 1085.76
#Mann= 3 , 0 , 0
    10.1      .1       0   293.1    .045       0   313.1     .06       0
Bank Sta=293.1,313.1
XS Rating Curve= 0 ,0
Exp/Cntr=0.3,0.1

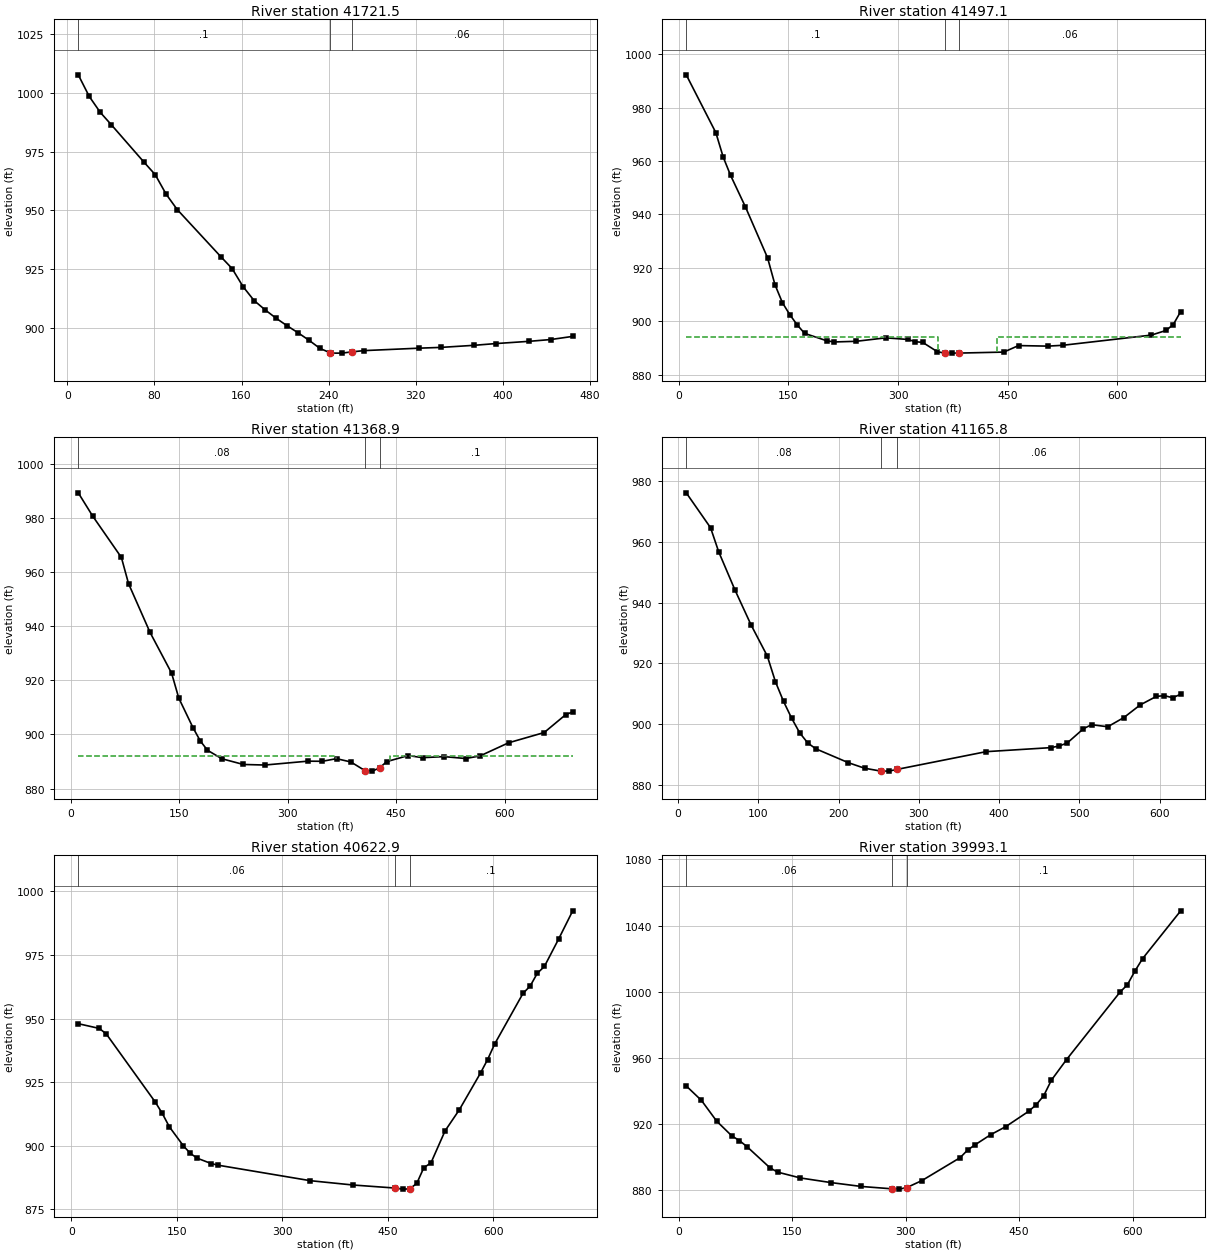
Type RM Length L Ch R = 1 ,41721.5 ,304,224.4,198.8
XS GIS Cut Line= 2
     1627484.833      335203.422     1627948.837      335198.129
#Sta/Elev= 30
    10.1 1007.72    20.2   998.5    30.3  991.73    40.4  986.48    70.6  970.43
    80.7  965.22    90.8  956.85   100.9  950.35   141.2  930.14   151.3  925.21
   161.4  917.48   171.5  911.57   181.6  907.62   191.7  904.04   201.8  900.83
   211.8  897.86   221.9  894.66     232  891.17   241.2 889.348   242.1  889.17
   252.2  889.17   261.2  889.71   272.4  890.24   322.8  891.28     343  891.61
   373.2  892.49   393.4  893.24   423.7  894.19   443.9  894.96     464   896.3
#Mann= 3 , 0 , 0
    10.1      .1       0   241.2    .045       0   261.2     .06       0
Bank Sta=241.2,261.2
XS Rating Curve= 0 ,0
Exp/Cntr=0.3,0.1

Type RM Length L Ch R = 1 ,41497.1 ,76.1,128.2,127.7
XS GIS Cut Line= 4
     1627566.075      335630.596      1627738.07      335628.144
     1627909.214       335207.24     1627969.445      335210.108
#Sta/Elev= 30
    10.1  992.31    50.6  970.65    60.7  961.48    70.8  954.63    91.1  942.83
   121.4  923.75   131.5   913.7   141.7  906.95   151.8  902.47   161.9  898.66
     172  895.46   202.3   892.7   212.4  892.24   242.7  892.49   283.1  893.79
   313.4  893.18   323.5  892.34   333.6  892.09   353.8  888.58     364  888.07
     374  888.06     384  888.08   444.6  888.45   464.8  890.89   505.2  890.68
   525.4     891   646.5  894.81   666.6  896.55   676.6  898.78   686.7  903.65
#Mann= 3 , 0 , 0
    10.1      .1       0     364    .045       0     384     .06       0
#XS Ineff= 2 , 0
       0     355     894     435       0     894
Permanent Ineff=
       F       F
Bank Sta=364,384
XS Rating Curve= 0 ,0
Exp/Cntr=0.3,0.1

Type RM Length L Ch R = 1 ,41368.9 ,176.3,203.1,228.5
XS GIS Cut Line= 4
     1627550.143      335674.882     1627768.255      335689.488
     1627926.423      335336.306     1627954.955      335252.228
#Sta/Elev= 30
     9.9  989.21    29.8  980.65    69.6  965.35    79.5  955.68   109.3  937.66
   139.1  922.65     149  913.46   168.9  902.41   178.9  897.58   188.8  894.17
   208.7  891.03   238.4  888.92   268.2  888.71   327.7  890.14   347.6  890.09
   367.4  891.06   387.3  889.84   407.1   886.6   417.1  886.46   427.1  887.68
   436.9  889.97   466.7  892.21   486.5  891.43   516.3  891.82     546  891.12
   565.9  892.05   605.6  896.92   654.9  900.71   684.5  907.27   694.4  908.35
#Mann= 3 , 0 , 0
     9.9     .08       0   407.1    .045       0   427.1      .1       0
#XS Ineff= 2 , 0
       0  367.33     892     442       0     892
Permanent Ineff=
       F       F
Bank Sta=407.1,427.1
XS Rating Curve= 0 ,0
Exp/Cntr=0.3,0.1

Type RM Length L Ch R = 1 ,41165.8 ,525.1,542.9,560.6
XS GIS Cut Line= 2
     1627576.986       335680.88     1628201.129      335729.832
#Sta/Elev= 30
    10.1  976.07    40.4  964.59    50.5   956.7    70.7  944.18    90.9  932.61
   111.1  922.39   121.2  913.97   131.3  907.49   141.4  901.96   151.5  897.13
   161.6  893.78   171.7  891.88   212.1  887.33   232.2  885.52   252.5  884.57
   262.5  884.56   272.5  885.12   383.7  890.96   464.5  892.29   474.6  892.82
   484.7   893.8   504.9  898.49     515  899.83   535.2  899.15   555.4  902.19
   575.6  906.32   595.8  909.14   605.9  909.38     616  908.69   626.1  909.84
#Mann= 3 , 0 , 0
    10.1     .08       0   252.5    .045       0   272.5     .06       0
Bank Sta=252.5,272.5
XS Rating Curve= 0 ,0
Exp/Cntr=0.3,0.1

Type RM Length L Ch R = 1 ,40622.9 ,633.5,629.8,626.1
XS GIS Cut Line= 3
     1627450.526      335803.261     1627664.692      335884.848
     1627972.685       336258.11
#Sta/Elev= 30
      10  947.97    39.9  946.11    49.8  943.96   119.6  917.15   129.5  912.71
   139.5  907.48   159.4  900.02   169.4  897.02   179.4  895.11   199.3  893.01
   209.3  892.37   340.1   886.3   400.6  884.61   461.1   883.4   471.1  882.99
   481.1  883.08   491.3  885.21   501.4  891.43   511.5  893.29   531.6  905.88
   551.8  914.13     582   928.6   592.1   933.9   602.2  940.03   642.5  959.91
   652.6  962.76   662.7  967.75   672.8  970.44   692.9  981.13   713.1   992.3
#Mann= 3 , 0 , 0
      10     .06       0   461.1    .045       0   481.1      .1       0
Bank Sta=461.1,481.1
XS Rating Curve= 0 ,0
Exp/Cntr=0.3,0.1

Type RM Length L Ch R = 1 ,39993.1 ,436.9,436.1,435.2
XS GIS Cut Line= 2
     1627208.925      336188.127      1627690.59      336644.457
#Sta/Elev= 30
    10.1  943.12    30.2  934.37    50.3  921.86    70.4   912.9    80.4  910.08
    90.5  906.38   120.6   893.7   130.7  891.05   160.8  887.51   201.1  884.72
   241.3  882.37   281.5  880.95   291.5  880.75   301.5  881.68   321.7  885.96
     372  899.76     382   904.4   392.1  907.64   412.2   913.6   432.3  918.52
   462.4  927.73   472.5  931.73   482.5  937.21   492.6   946.6   512.7  959.09
   583.1  999.71   593.1 1004.34   603.2  1012.7   613.2 1020.12   663.5 1048.97
#Mann= 3 , 0 , 0
    10.1     .06       0   281.5    .045       0   301.5      .1       0
Bank Sta=281.5,301.5
XS Rating Curve= 0 ,0
Exp/Cntr=0.3,0.1

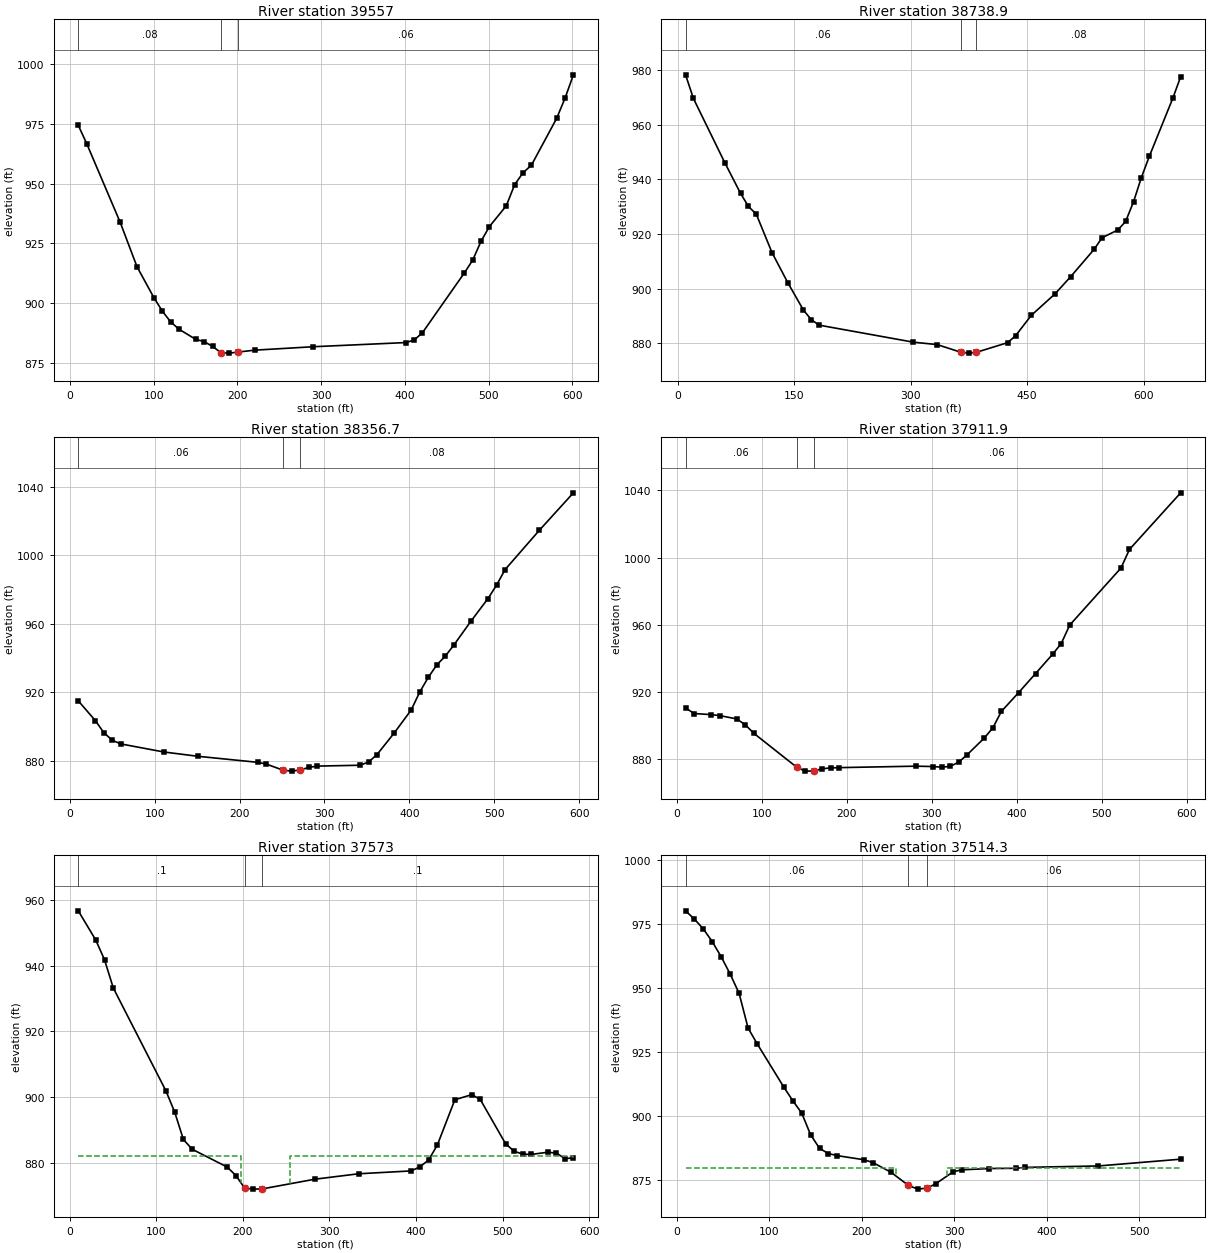
Type RM Length L Ch R = 1 ,39557   ,824.2,818.1,802.7
XS GIS Cut Line= 2
     1627001.401       336539.04     1627468.883      336916.928
#Sta/Elev= 30
      10  974.49      20  966.87    60.1  933.79    80.1  915.25   100.2  902.33
   110.2  896.72   120.2  892.16   130.2  889.08   150.3   884.8   160.3  883.89
   170.3  881.85   180.4  879.24   190.4  879.05   200.4  879.47   220.4  880.29
   290.5  881.73   400.7  883.47   410.8  884.48   420.8  887.56   470.9  912.65
   480.9  918.04   490.9  925.98   500.9  932.11     521  940.81     531  949.68
     541  954.64     551  957.81   581.1  977.42   591.1  985.86   601.1  995.67
#Mann= 3 , 0 , 0
      10     .08       0   180.4    .045       0   200.4     .06       0
Bank Sta=180.4,200.4
XS Rating Curve= 0 ,0
Exp/Cntr=0.3,0.1

Type RM Length L Ch R = 1 ,38738.9 ,381.5,382.3,383
XS GIS Cut Line= 2
     1626436.803      337029.111     1626977.319      337386.056
#Sta/Elev= 30
    10.1  978.21    20.2  969.57    60.7  946.02      81   934.8    91.1  930.05
   101.2  927.21   121.5  913.12   141.7   902.2   161.9  892.13   172.1  888.61
   182.2  886.62   303.6  880.39     334  879.52   364.5  876.73   374.5  876.39
   384.5  876.68   425.1  880.24   435.2  882.81   455.4  890.22   485.8  898.05
     506  904.34   536.4  914.42   546.5  918.62   566.8  921.43   576.9  924.61
     587  931.76   597.1  940.63   607.3  948.37   637.6  969.65   647.7  977.52
#Mann= 3 , 0 , 0
    10.1     .06       0   364.5    .045       0   384.5     .08       0
Bank Sta=364.5,384.5
XS Rating Curve= 0 ,0
Exp/Cntr=0.3,0.1

Type RM Length L Ch R = 1 ,38356.7 ,454.4,444.8,435.2
XS GIS Cut Line= 2
     1626302.184      337392.174     1626808.025      337702.206
#Sta/Elev= 30
    10.1  915.08    30.2  903.56    40.2  896.51    50.3  892.04    60.3  889.95
   110.6  885.28   150.8  882.75   221.2  879.24   231.3  878.25   251.5  874.61
   261.5  874.09   271.5  874.78   281.6  876.26   291.6  877.03   341.9  877.52
     352  879.38     362  883.78   382.1  896.25   402.2  909.74   412.3  920.23
   422.3  928.74   432.4  936.08   442.5  941.24   452.5  947.66   472.6  961.56
   492.7  974.78   502.8  982.61   512.8  991.65   553.1 1014.56   593.3 1036.46
#Mann= 3 , 0 , 0
    10.1     .06       0   251.5    .045       0   271.5     .08       0
Bank Sta=251.5,271.5
XS Rating Curve= 0 ,0
Exp/Cntr=0.3,0.1

Type RM Length L Ch R = 1 ,37911.9 ,338.1,338.9,339.3
XS GIS Cut Line= 2
     1626165.525      337904.135     1626757.033      337944.929
#Sta/Elev= 30
      10  910.45    20.1  907.12    40.2  906.47    50.2   905.9    70.3  903.89
    80.4  900.37    90.4  895.33   140.7  875.21   150.7  872.82   160.7   872.9
   170.8  874.22   180.9  874.74   190.9   874.9   281.4  875.78   301.5  875.54
   311.5  875.18   321.6  875.65   331.6  878.18   341.7  882.67   361.8  892.58
   371.8  898.62   381.9  908.42     402   919.5   422.1  930.94   442.2  942.47
   452.2  948.72   462.3   959.8   522.6  993.74   532.6 1004.83   592.9 1038.54
#Mann= 3 , 0 , 0
      10     .06       0   140.7    .045       0   160.7     .06       0
Bank Sta=140.7,160.7
XS Rating Curve= 0 ,0
Exp/Cntr=0.3,0.1

Type RM Length L Ch R = 1 ,37573   ,60.8,58.7,56.8
XS GIS Cut Line= 3
     1626233.717      338214.967     1626678.156      338230.456
     1626796.581      338298.908
#Sta/Elev= 30
    10.1  956.61    30.3  947.71    40.4  941.72    50.5  933.17   111.2  901.94
   121.3  895.51   131.4  887.16   141.5   884.2   181.9  878.79     192  876.21
   202.2  872.36   212.2  872.08   222.2  872.14     283  875.09   333.5  876.74
   394.2  877.61   404.3  878.84   414.4  880.93   424.5  885.49   444.7  899.23
   464.3  900.78     474  899.32   503.3  885.84   513.1   883.6   522.9  882.71
   532.6  882.61   552.2   883.3     562     883   571.7  881.38   581.5  881.53
#Mann= 3 , 0 , 0
    10.1      .1       0   202.2    .045       0   222.2      .1       0
#XS Ineff= 2 , 0
       0     198     882     255       0     882
Permanent Ineff=
       F       F
Bank Sta=202.2,222.2
XS Rating Curve= 0 ,0
Exp/Cntr=0.3,0.1

Type RM Length L Ch R = 1 ,37514.3 ,430.7,447.4,464.1
XS GIS Cut Line= 4
     1626214.477      338273.318     1626417.217      338275.483
     1626571.435      338271.578     1626726.438      338377.342
#Sta/Elev= 30
     9.7  980.18    19.3  976.94      29  973.06    38.6  968.13    48.3  962.18
    57.9  955.52    67.6  947.95    77.2   934.5    86.9  928.42   115.9   911.4
   125.5  906.16   135.2  901.29   144.8  892.86   154.5  887.52   164.1   885.5
   173.8  884.68   202.8  883.07   212.4  881.95   231.7   878.2   250.6  873.06
   260.6  871.63   270.6  872.03   279.9  873.69   299.2  878.47   308.8  879.17
   337.7  879.65   366.9  879.76   376.8  880.11   455.8  880.67   544.7  883.31
#Mann= 3 , 0 , 0
     9.7     .06       0   250.6    .045       0   270.6     .06       0
#XS Ineff= 2 , 0
       0     237     880     292       0     880
Permanent Ineff=
       F       F
Bank Sta=250.6,270.6
XS Rating Curve= 0 ,0
Exp/Cntr=0.3,0.1

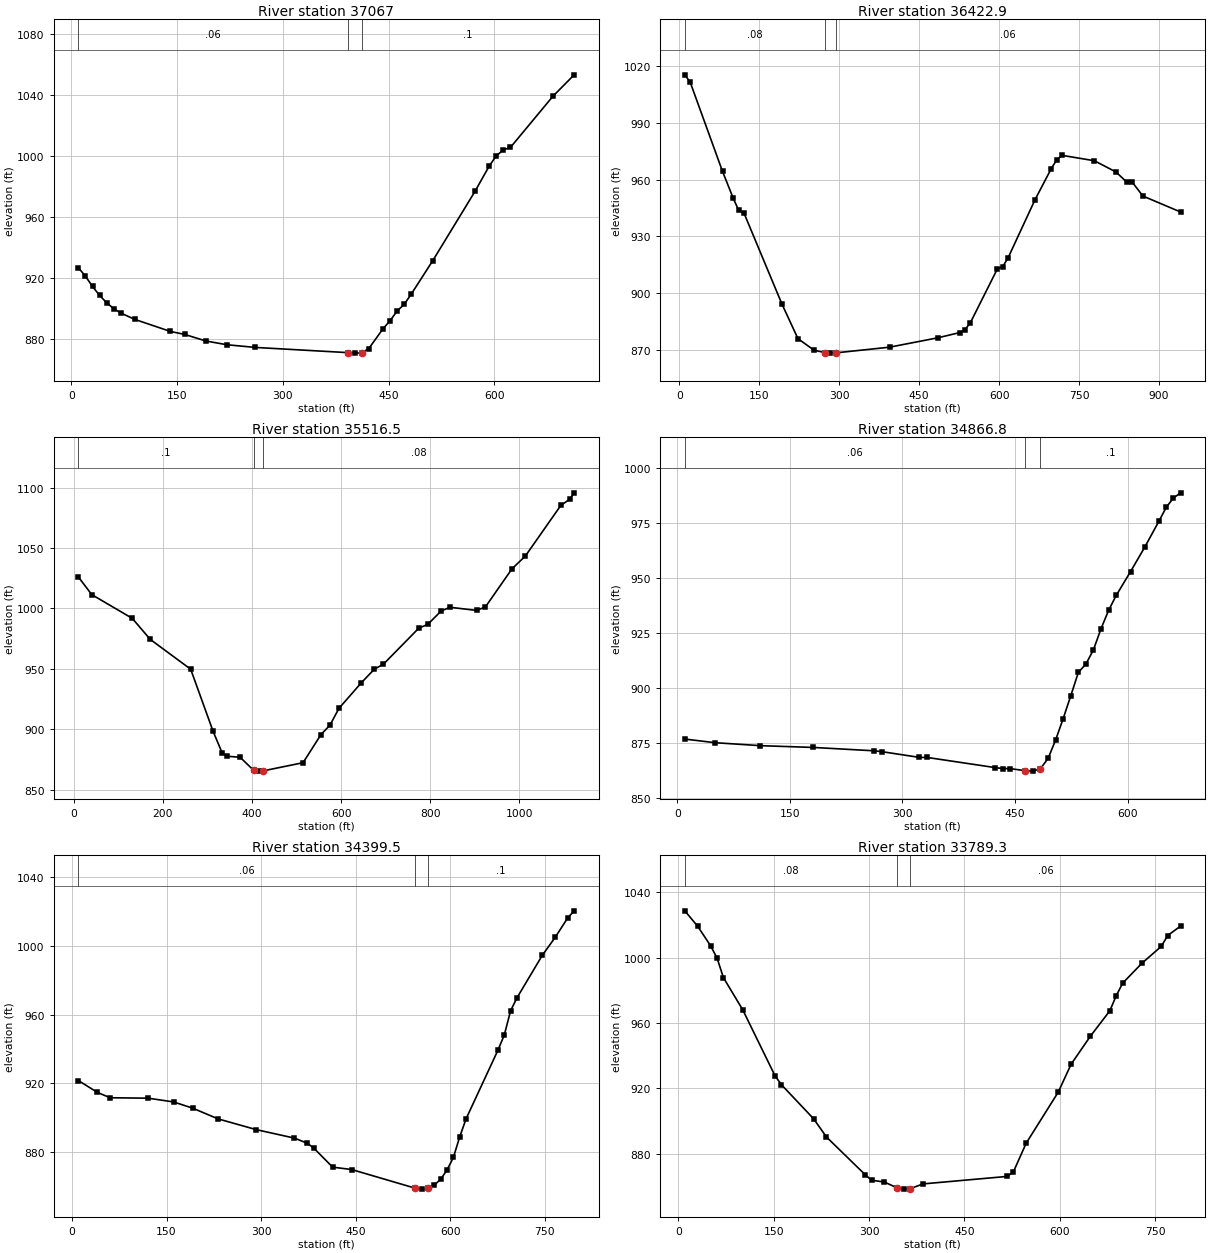
Type RM Length L Ch R = 1 ,37067   ,638.7,644.1,649.4
XS GIS Cut Line= 2
      1626096.48      338381.151     1626575.805      338909.429
#Sta/Elev= 30
      10   926.9    20.1  921.35    30.1  914.59    40.2  908.75    50.2  903.93
    60.3  900.06    70.3  897.19    90.4  892.97   140.7  885.14   160.7  883.21
   190.9  878.89     221  876.42   261.2  874.67   391.9  871.28   401.9  870.94
   411.9  871.07     422  873.91   442.1  886.86   452.1  892.14   462.2  898.54
   472.2  902.89   482.2  909.59   512.4  931.26   572.7  976.95   592.8  993.48
   602.8 1000.18   612.9 1004.07   622.9 1005.68   683.2 1039.22   713.3 1053.25
#Mann= 3 , 0 , 0
      10     .06       0   391.9    .045       0   411.9      .1       0
Bank Sta=391.9,411.9
XS Rating Curve= 0 ,0
Exp/Cntr=0.3,0.1

Type RM Length L Ch R = 1 ,36422.9 ,885.4,906.4,927.4
XS GIS Cut Line= 2
     1625655.604      338642.501     1626080.406       339481.77
#Sta/Elev= 30
    10.1 1015.25    20.2 1011.38    80.9   964.3   101.1  950.08   111.3  943.71
   121.4  942.19   192.2  894.49   222.5  876.08   252.9  869.96   273.2  868.76
   283.2  868.46   293.2  868.59   394.5   871.6   485.5  876.57     526  879.29
   536.1  880.88   546.2  884.56   596.8  912.93   606.9  914.12     617   918.8
   667.6  949.48   697.9  965.77     708  970.33   718.1  972.78   778.8  969.94
   819.3     964   839.5   958.7   849.6  958.75   869.9  951.32   940.7  942.89
#Mann= 3 , 0 , 0
    10.1     .08       0   273.2    .045       0   293.2     .06       0
Bank Sta=273.2,293.2
XS Rating Curve= 0 ,0
Exp/Cntr=0.3,0.1

Type RM Length L Ch R = 1 ,35516.5 ,665.3,649.7,634.1
XS GIS Cut Line= 3
     1625209.211       338271.59     1624880.892      338767.986
     1624944.803      339291.938
#Sta/Elev= 30
    10.1 1026.03    40.3 1011.35   131.1  991.73   171.5  974.29   262.3   949.6
   312.7  898.05   332.9  880.34     343   877.6   373.2  876.69   403.6  865.92
   413.6  865.23   423.6  865.35   514.5   872.2   554.8  895.51     575  903.36
   595.1  917.21   644.9  938.22   674.8  949.75   694.7   953.7   774.4  983.63
   794.3  986.67   824.2  997.72   844.1 1000.88   903.9   998.3   923.8 1001.15
   983.6  1032.8  1013.4 1043.27  1093.1 1085.23    1113 1090.32    1123 1095.64
#Mann= 3 , 0 , 0
    10.1      .1       0   403.6    .045       0   423.6     .08       0
Bank Sta=403.6,423.6
XS Rating Curve= 0 ,0
Exp/Cntr=0.3,0.1

Type RM Length L Ch R = 1 ,34866.8 ,488.2,467.3,446.5
XS GIS Cut Line= 3
     1624371.916      338058.029     1624470.547      338634.342
     1624507.262       338711.85
#Sta/Elev= 30
    10.1  876.62    50.4  874.97   110.9  873.62   181.5  872.81   262.1  871.29
   272.2  870.92   322.6  868.29   332.7  868.28   423.4  863.66   433.5  863.22
   443.6  863.18   463.8  862.24   473.8  862.05   483.8  863.14     494  867.85
     504   876.2   514.1  885.95   524.2   896.3   534.3  906.92   544.4  910.76
   554.4  917.18   564.5   926.8   574.6  935.13   584.7   941.9   603.8  952.73
   622.8  963.87   641.9  975.83   651.4  981.96   660.9  986.17   670.5  988.52
#Mann= 3 , 0 , 0
    10.1     .06       0   463.8    .045       0   483.8      .1       0
Bank Sta=463.8,483.8
XS Rating Curve= 0 ,0
Exp/Cntr=0.3,0.1

Type RM Length L Ch R = 1 ,34399.5 ,612.6,610.1,607.7
XS GIS Cut Line= 2
     1623727.842      338637.695     1624470.222      338925.833
#Sta/Elev= 30
    10.1   921.7    40.3   914.8    60.5  911.69     121  911.43   161.3  909.24
   191.5  905.62   231.8  899.39   292.3  893.15   352.8  888.23     373  885.28
     383   882.6   413.3  871.37   443.5  869.97   544.4  859.12   554.4  858.59
   564.4  858.99   574.6  860.95   584.7  864.35   594.7  869.71   604.8  876.99
   614.9  889.06     625  899.51   675.4  939.28   685.5  948.12   695.5  962.22
   705.6  969.73   745.9  994.52   766.1 1004.81   786.3  1016.3   796.3  1020.3
#Mann= 3 , 0 , 0
    10.1     .06       0   544.4    .045       0   564.4      .1       0
Bank Sta=544.4,564.4
XS Rating Curve= 0 ,0
Exp/Cntr=0.3,0.1

Type RM Length L Ch R = 1 ,33789.3 ,689.2,667.4,645.7
XS GIS Cut Line= 2
     1623456.654      339108.886     1624222.762      339302.108
#Sta/Elev= 30
    10.1 1028.73    30.4 1019.26    50.6 1007.36    60.8  999.84    70.9  987.77
   101.3  968.07   151.9  927.79   162.1  922.23   212.7  901.38     233  890.18
   293.8  867.13   303.9  863.75   324.1   862.6   344.5  858.99   354.5  858.27
   364.5  858.52   384.9  861.47   516.6  866.03   526.7  868.57     547   886.3
   597.6  917.71   617.9  934.82   648.3  952.02   678.7  967.47   688.8  976.72
   698.9  984.43   729.3  996.65   759.7 1006.97   769.8  1013.6   790.1 1019.41
#Mann= 3 , 0 , 0
    10.1     .08       0   344.5    .045       0   364.5     .06       0
Bank Sta=344.5,364.5
XS Rating Curve= 0 ,0
Exp/Cntr=0.3,0.1

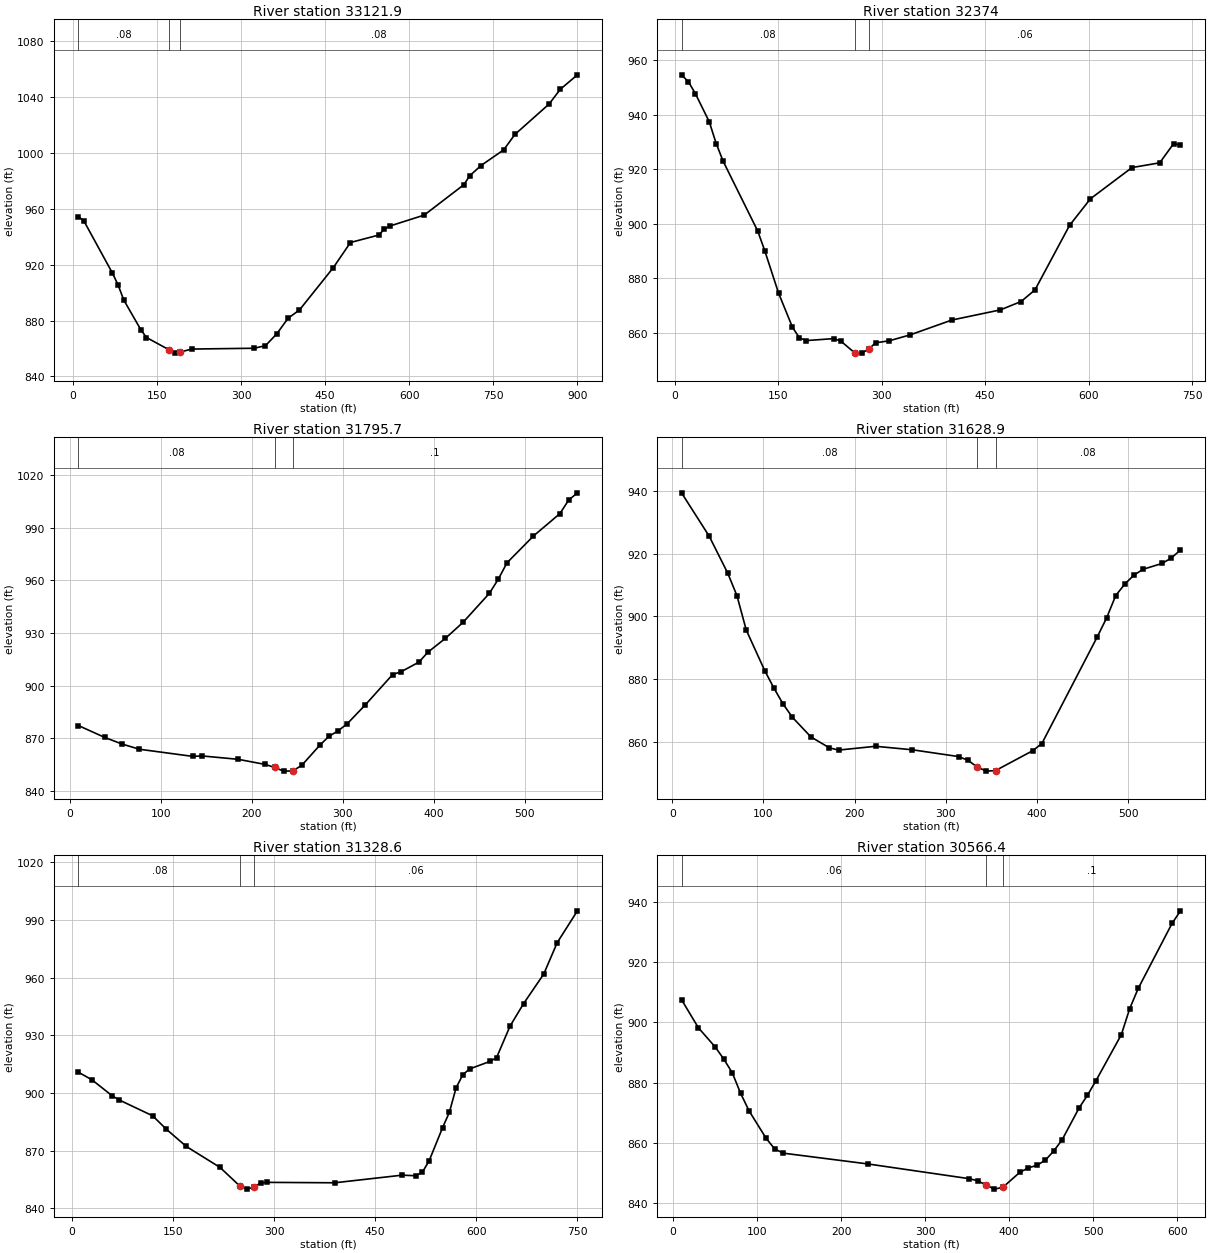
Type RM Length L Ch R = 1 ,33121.9 ,726.6,747.9,769.2
XS GIS Cut Line= 3
     1623900.806      339879.542     1624233.423      339512.725
     1624636.325      339552.957
#Sta/Elev= 30
    10.1  954.54    20.2  951.04    70.7  913.99    80.8  905.43    90.9   894.7
   121.3  873.43   131.4  867.85   171.9     859   181.9  856.66   191.9  857.49
   212.2  859.58   323.4  860.16   343.6  861.99   363.8  870.48     384  881.69
   404.2  887.56   464.8  918.01   495.2  935.94   545.8  941.29   555.9  945.66
     566  947.81   626.8  955.59   697.6  977.38   707.7  983.65     728  991.07
   768.5 1002.32   788.7 1013.44   849.5 1035.17   869.7 1045.82   900.1 1056.11
#Mann= 3 , 0 , 0
    10.1     .08       0   171.9    .045       0   191.9     .08       0
Bank Sta=171.9,191.9
XS Rating Curve= 0 ,0
Exp/Cntr=0.3,0.1

Type RM Length L Ch R = 1 ,32374   ,563.6,578.3,593
XS GIS Cut Line= 2
     1624029.976       340325.24     1624744.801      340488.559
#Sta/Elev= 30
      10  954.54    20.1  951.98    30.1  947.64    50.2  937.36    60.3  929.33
    70.3   922.9   120.5  897.28   130.6  890.12   150.7  874.53   170.8  862.05
   180.8   858.2   190.8  857.17     231  857.89   241.1  856.94   261.2  852.64
   271.2  852.57   281.2  854.02   291.3  856.34   311.4  857.11   341.5  859.27
   401.8  864.69   472.1  868.41   502.2  871.48   522.3  875.73   572.5   899.4
   602.7  909.12   662.9  920.56   703.1   922.3   723.2  929.29   733.2  928.87
#Mann= 3 , 0 , 0
      10     .08       0   261.2    .045       0   281.2     .06       0
Bank Sta=261.2,281.2
XS Rating Curve= 0 ,0
Exp/Cntr=0.3,0.1

Type RM Length L Ch R = 1 ,31795.7 ,172.9,166.8,160.7
XS GIS Cut Line= 4
     1624048.333       340712.78     1624117.242      340792.433
     1624263.537      340994.338      1624466.71         340997.
#Sta/Elev= 30
     9.6  877.15    38.3  870.43    57.4  866.64    76.6  863.66   135.2  859.59
   145.2  859.86   185.1  857.92     215  854.98     225  853.31     235  851.19
     245   851.3   254.9  854.48   274.9  866.05   284.8  871.03   294.8  874.16
   304.8  878.15   324.7  888.94   354.7  906.22   364.3  907.93   383.7  913.34
   393.4  918.95   412.7  926.88   432.1     936   461.1  952.59   470.8  960.58
   480.4  969.96   509.5  985.25   538.5  997.99   548.2 1005.74   557.8 1009.85
#Mann= 3 , 0 , 0
     9.6     .08       0     225    .045       0     245      .1       0
Bank Sta=225,245
XS Rating Curve= 0 ,0
Exp/Cntr=0.3,0.1

Type RM Length L Ch R = 1 ,31628.9 ,315.3,300.3,285.2
XS GIS Cut Line= 2
     1623783.174      340786.209     1624230.049      341119.458
#Sta/Elev= 30
    10.1  939.33    40.5   925.5    60.8  913.75    70.9  906.59    81.1  895.65
   101.4   882.7   111.5  877.13   121.6  872.04   131.8  867.83     152  861.61
   172.3  858.12   182.4   857.4     223  858.61   263.5  857.49   314.2  855.33
   324.3  854.16   334.6  851.99   344.6   850.7   354.6  850.87   395.3  857.19
   405.4  859.47   466.2  893.45   476.4  899.44   486.5  906.63   496.6  910.33
   506.8  913.22   516.9  915.02   537.2  916.83   547.3  918.53   557.5  921.13
#Mann= 3 , 0 , 0
    10.1     .08       0   334.6    .045       0   354.6     .08       0
Bank Sta=334.6,354.6
XS Rating Curve= 0 ,0
Exp/Cntr=0.3,0.1

Type RM Length L Ch R = 1 ,31328.6 ,769.3,762.2,755
XS GIS Cut Line= 2
      1623613.88       341226.78     1624360.404      341153.352
#Sta/Elev= 30
      10  910.81      30  906.86      60  898.56      70  896.45     120  888.14
     140  881.26     170  872.17     220  861.26     250  851.35     260  849.97
     270  850.99     280  853.15     290  853.49   390.1  853.27   490.1  857.24
   510.1  856.93   520.1  858.76   530.1  864.72   550.1  882.01   560.1  889.92
   570.1  902.69   580.1  909.53   590.1  912.52   620.1  916.42   630.1  918.36
   650.1  934.82   670.1  946.48   700.1  961.92   720.1  978.29   750.1  994.84
#Mann= 3 , 0 , 0
      10     .08       0     250    .045       0     270     .06       0
Bank Sta=250,270
XS Rating Curve= 0 ,0
Exp/Cntr=0.3,0.1

Type RM Length L Ch R = 1 ,30566.4 ,687.8,696.8,709.1
XS GIS Cut Line= 2
     1624025.896      341865.202     1624570.492      341604.122
#Sta/Elev= 30
    10.1  907.49    30.2  898.17    50.3  891.78    60.4   887.8    70.5  883.25
    80.5  876.41    90.6  870.59   110.7  861.59   120.8  858.08   130.9  856.64
   231.5  853.07   352.3  848.18   362.4  847.49   372.5  846.07   382.5  844.71
   392.5  845.32   412.7  850.27   422.8  851.75   432.8  852.58   442.9  854.25
     453  857.32     463  861.03   483.2  871.59   493.2  875.81   503.3  880.63
   533.5  895.88   543.5  904.53   553.6  911.21   593.9  932.77   603.9  936.93
#Mann= 3 , 0 , 0
    10.1     .06       0   372.5    .045       0   392.5      .1       0
Bank Sta=372.5,392.5
XS Rating Curve= 0 ,0
Exp/Cntr=0.3,0.1

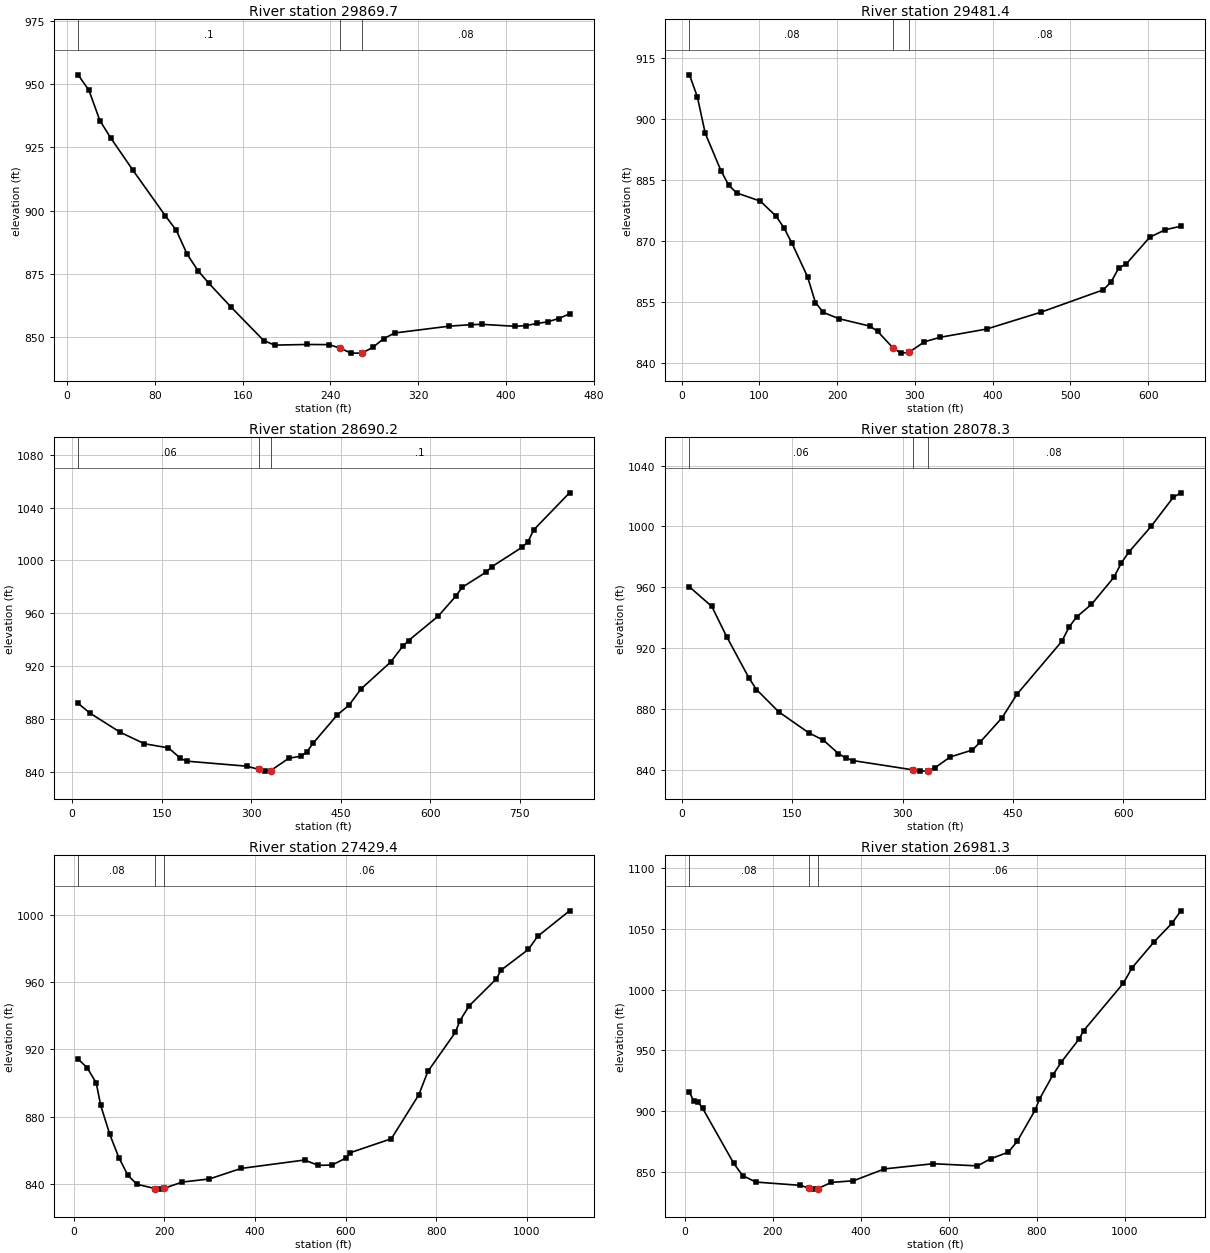
Type RM Length L Ch R = 1 ,29869.7 ,399.2,388.3,377.4
XS GIS Cut Line= 2
      1624193.15      342295.575      1624650.04       342328.21
#Sta/Elev= 30
      10  953.61    19.9  947.47    29.9  935.48    39.8  928.64    59.7   916.1
    89.6  897.89    99.6  892.14   109.5  882.66   119.5  876.13   129.4  871.17
   149.4  861.88   179.2  848.63   189.2  846.82   219.1  847.07     239  847.01
   248.9  845.61   258.9  843.65   268.9  843.66   278.8  845.95   288.8   849.4
   298.7  851.61   348.5  854.31   368.4   854.9   378.4  855.02   408.3  854.26
   418.2  854.51   428.2  855.36   438.1     856   448.1  857.32   458.1  859.14
#Mann= 3 , 0 , 0
      10      .1       0   248.9    .045       0   268.9     .08       0
Bank Sta=248.9,268.9
XS Rating Curve= 0 ,0
Exp/Cntr=0.3,0.1

Type RM Length L Ch R = 1 ,29481.4 ,769.7,791.1,812.4
XS GIS Cut Line= 3
     1624174.793      342736.147     1624353.992      342702.946
     1624762.222      342491.385
#Sta/Elev= 30
    10.1  910.85    20.2  905.48    30.4  896.49    50.6  887.32    60.7  883.71
    70.9  881.84   101.2  879.84   121.5  876.14   131.6  873.29   141.7  869.59
     162  861.23   172.1  854.93   182.2  852.52   202.2  850.97   242.2  849.14
   252.2  847.83   272.2  843.71   282.2  842.51   292.2  842.68   312.2  845.28
   332.2  846.39   392.2  848.42   462.1  852.56   542.1  858.04   552.1  859.91
   562.1  863.39   572.1  864.48   602.1  870.98   622.1  872.82     642  873.67
#Mann= 3 , 0 , 0
    10.1     .08       0   272.2    .045       0   292.2     .08       0
Bank Sta=272.2,292.2
XS Rating Curve= 0 ,0
Exp/Cntr=0.3,0.1

Type RM Length L Ch R = 1 ,28690.2 ,634.2,611.9,589.5
XS GIS Cut Line= 3
     1624154.396      343131.845     1624523.576      343378.507
     1624912.601      343363.933
#Sta/Elev= 30
    10.1  891.67    30.3  884.22    80.7   869.8   121.1  861.15   161.5  857.98
   181.6  850.11   191.7  847.96   292.6  844.14   312.9  841.75   322.9   840.4
   332.9  840.86   363.3  850.21   383.5  851.66   393.5  855.04   403.6  861.42
     444  882.87     464  890.36   483.9  902.57   533.8  923.03   553.8  934.87
   563.8   939.3   613.7  957.88   643.6  973.31   653.6   979.6   693.5  991.03
   703.5  995.25   753.4 1009.76   763.4 1013.83   773.4  1023.1   833.3 1051.11
#Mann= 3 , 0 , 0
    10.1     .06       0   312.9    .045       0   332.9      .1       0
Bank Sta=312.9,332.9
XS Rating Curve= 0 ,0
Exp/Cntr=0.3,0.1

Type RM Length L Ch R = 1 ,28078.3 ,634.6,648.9,663.2
XS GIS Cut Line= 2
     1624134.626      343936.047     1624727.851      343607.231
#Sta/Elev= 30
    10.1  960.27    40.5  947.39    60.7  927.53    91.1  900.28   101.2  892.77
   131.6  878.04   172.1  864.35   192.3  859.42   212.6  850.66   222.7  847.72
   232.8  845.99   313.9  839.92   323.9  839.08   333.9  839.31   344.2  841.35
   364.4  848.34   394.8  852.96   404.9  857.91   435.3  874.26   455.5  889.68
   516.3  924.37   526.4  933.88   536.5  940.47   556.8  948.77   587.2  966.52
   597.3  975.92   607.4  983.04   637.8 1000.03   668.1 1019.24   678.3 1022.13
#Mann= 3 , 0 , 0
    10.1     .06       0   313.9    .045       0   333.9     .08       0
Bank Sta=313.9,333.9
XS Rating Curve= 0 ,0
Exp/Cntr=0.3,0.1

Type RM Length L Ch R = 1 ,27429.4 ,426.4,448.1,470
XS GIS Cut Line= 3
      1624386.92      344325.061     1624844.453      344428.931
     1625417.465      344678.067
#Sta/Elev= 30
      10  914.19    29.9  909.12    49.9  900.07    59.9  886.66    79.9   869.4
    99.8  855.69   119.8  845.11   139.8  839.79   179.7  837.23   189.7   836.9
   199.7  837.38   239.6   841.1   299.5  842.94   369.4   849.2   509.5   854.2
   539.7  851.04     570  851.21   600.2  855.29   610.3  858.56     701  866.86
   761.4   892.9   781.6  906.89   842.1  930.08   852.1  936.93   872.3  945.77
   932.8  961.96   942.8  967.06  1003.3  979.42  1023.5  987.14    1094 1002.37
#Mann= 3 , 0 , 0
      10     .08       0   179.7    .045       0   199.7     .06       0
Bank Sta=179.7,199.7
XS Rating Curve= 0 ,0
Exp/Cntr=0.3,0.1

Type RM Length L Ch R = 1 ,26981.3 ,508,515.2,522.4
XS GIS Cut Line= 3
     1624299.214      344435.203     1624470.749      345056.753
     1624849.436      345355.716
#Sta/Elev= 30
    10.1  915.29    20.1  908.22    30.2  907.16    40.3  902.06   110.8  856.85
     131  846.79   161.2  841.46   261.9  838.77   282.2  836.48   292.2  835.65
   302.2   836.1   332.5  841.19   382.8   842.5   453.4   852.3   564.2  856.57
   664.9  854.78     695  860.69   735.2  866.08   755.4  875.07   795.6  900.45
   805.6  909.55   835.8  929.28   855.9  940.44   896.1   959.3   906.1  966.02
   996.6 1005.16  1016.7 1018.02    1067 1039.45  1107.2 1054.57  1127.3 1064.78
#Mann= 3 , 0 , 0
    10.1     .08       0   282.2    .045       0   302.2     .06       0
Bank Sta=282.2,302.2
XS Rating Curve= 0 ,0
Exp/Cntr=0.3,0.1