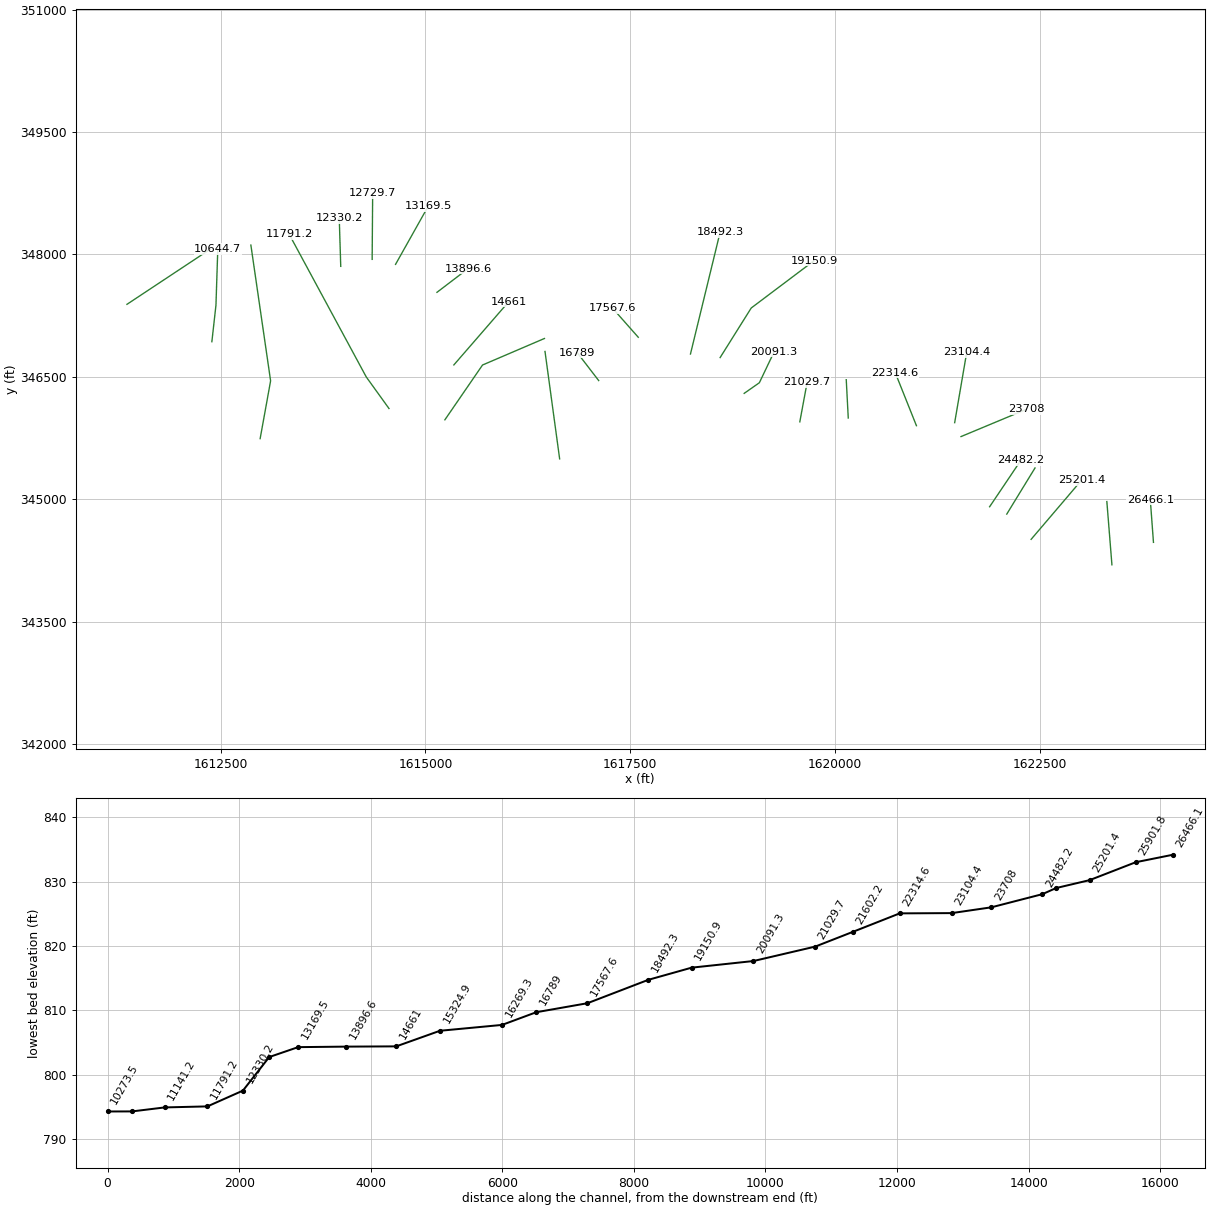
HEC-RAS study stfrktwl1.prj: stfrktwl1

--- stfrktwl1.g01 (geometry) --- (continued)

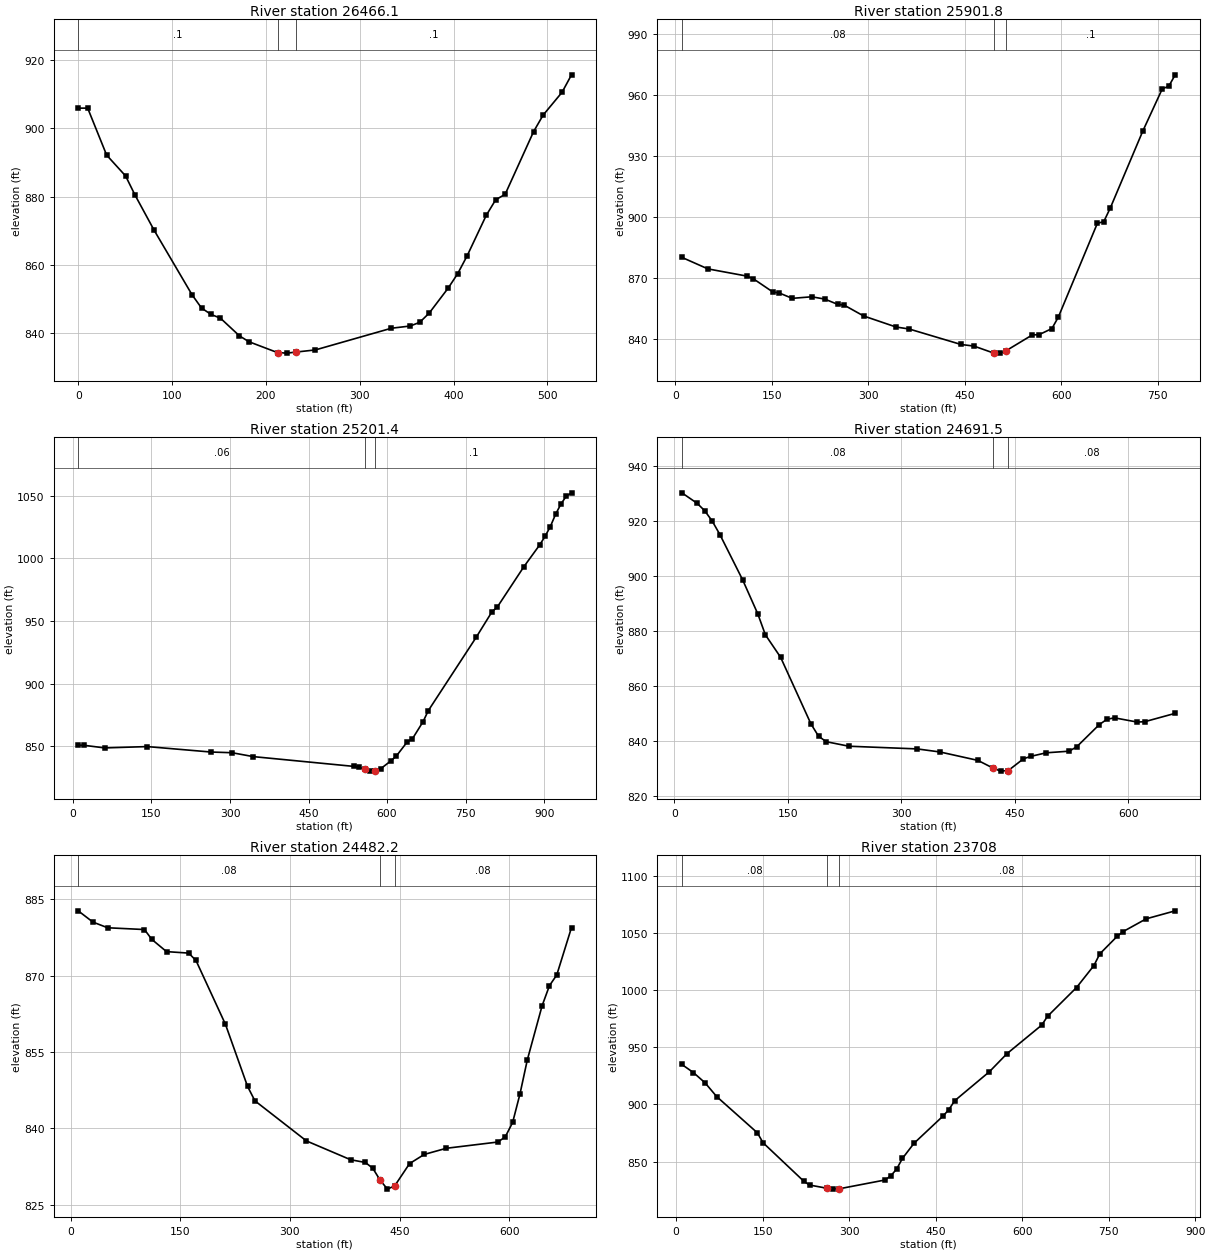
Type RM Length L Ch R = 1 ,26466.1 ,564,564.3,564.5
XS GIS Cut Line= 2
     1623889.237      344471.918     1623850.483      344996.117
#Sta/Elev= 30
       0  905.96    10.1  905.96    30.3  892.19    50.5  886.08    60.6  880.45
    80.9  870.17   121.3  851.26   131.4  847.37   141.5  845.51   151.6  844.39
   171.8  839.22   181.9   837.5   212.4  834.31   222.4  834.16   232.4  834.48
   252.7   835.1   333.6  841.45   353.8  842.11   363.9   843.2     374   845.9
   394.2  853.22   404.3  857.43   414.4  862.68   434.7  874.51   444.8   879.1
   454.9  880.71   485.2  899.08   495.3   903.9   515.5   910.6   525.6  915.72
#Mann= 3 , 0 , 0
       0      .1       0   212.4    .045       0   232.4      .1       0
Bank Sta=212.4,232.4
XS Rating Curve= 0 ,0
Exp/Cntr=0.3,0.1

Type RM Length L Ch R = 1 ,25901.8 ,716.1,700.4,684.8
XS GIS Cut Line= 2
     1623382.077      344197.067     1623320.166       344971.64
#Sta/Elev= 30
    10.1  880.06    50.5   874.4     111  870.87   121.1  869.56   151.4  863.06
   161.5  862.56   181.6  859.92   211.9  860.69   232.1  859.57   252.3  856.97
   262.4  856.58   292.7  851.25   343.1  845.83   363.3  844.87     444  837.25
   464.2  836.46   494.6  833.05   504.6     833   514.6  834.27     555  841.98
   565.1  842.04   585.3  845.06   595.4  850.77   655.9  896.74     666  897.67
   676.1  904.34   726.6  942.13   756.9  962.89     767  964.18     777  969.78
#Mann= 3 , 0 , 0
    10.1     .08       0   494.6    .045       0   514.6      .1       0
Bank Sta=494.6,514.6
XS Rating Curve= 0 ,0
Exp/Cntr=0.3,0.1

Type RM Length L Ch R = 1 ,25201.4 ,506.8,509.9,512.9
XS GIS Cut Line= 2
     1622395.627      344508.934     1623012.173       345234.76
#Sta/Elev= 30
    10.1  850.87    20.3  850.87    60.8  848.75   141.8  849.81   263.4  845.47
   303.9  844.91   344.5   841.8     537  833.98   547.1  833.19   557.4  831.57
   567.4  830.22   577.4  830.29   587.6  832.05   607.9   838.6     618   842.4
   638.3  853.43   648.4  856.01   668.7  869.65   678.8  878.52     770  936.88
   800.4   957.4   810.5  961.14   861.2  993.31   891.6 1010.81   901.7 1017.56
   911.8 1025.36   921.9 1035.22   932.1 1043.42   942.2  1049.6   952.3 1052.34
#Mann= 3 , 0 , 0
    10.1     .06       0   557.4    .045       0   577.4      .1       0
Bank Sta=557.4,577.4
XS Rating Curve= 0 ,0
Exp/Cntr=0.3,0.1

Type RM Length L Ch R = 1 ,24691.5 ,210.1,209.3,208.5
XS GIS Cut Line= 2
     1622098.395      344818.664     1622443.101      345383.657
#Sta/Elev= 30
      10   930.1    30.1   926.3    40.1  923.61    50.1  919.82    60.2  914.93
    90.3  898.46   110.3  886.11   120.3  878.52   140.4  870.36   180.5  846.15
   190.5   841.7   200.6  839.69   230.6  838.04   320.9  837.06     351  835.95
   401.1  832.89   421.2  830.08   431.2  828.99   441.2  829.19   461.3  833.47
   471.3  834.38   491.4  835.65   521.5  836.23   531.5  837.78   561.6  845.92
   571.6  847.82   581.6  848.35   611.7  846.81   621.7  846.96   661.8  849.99
#Mann= 3 , 0 , 0
      10     .08       0   421.2    .045       0   441.2     .08       0
Bank Sta=421.2,441.2
XS Rating Curve= 0 ,0
Exp/Cntr=0.3,0.1

Type RM Length L Ch R = 1 ,24482.2 ,786.5,774.3,761.7
XS GIS Cut Line= 2
     1621888.896       344908.26      1622270.63      345477.513
#Sta/Elev= 30
    10.1  882.75    30.2  880.54    50.4  879.42   100.8  879.07   110.9  877.13
     131  874.73   161.3  874.44   171.3     873   211.7  860.43   241.9  848.24
     252   845.4   322.5  837.52     383  833.82   403.2  833.28   413.3  832.15
   423.4  829.81   433.4  828.04   443.4  828.69   463.7  833.06   483.8  834.86
     514  836.07   584.6   837.3   594.7  838.31   604.8  841.15   614.8  846.72
   624.9  853.45   645.1  864.07   655.2  868.04   665.2  870.14   685.4  879.47
#Mann= 3 , 0 , 0
    10.1     .08       0   423.4    .045       0   443.4     .08       0
Bank Sta=423.4,443.4
XS Rating Curve= 0 ,0
Exp/Cntr=0.3,0.1

Type RM Length L Ch R = 1 ,23708   ,582.9,603.6,624.5
XS GIS Cut Line= 2
     1621539.723      345768.035        1622338.      346102.168
#Sta/Elev= 30
    10.1  934.98    30.2  927.87    50.3  918.93    70.4  906.93   140.9  875.26
   150.9  866.51   221.4  832.93   231.4  829.58   261.7  826.76   271.7     826
   281.7  826.18   362.3  833.99   372.3  837.68   382.4  843.49   392.4  852.82
   412.6  866.12   462.9  889.93   472.9  895.47     483  903.27   543.4  928.73
   573.6  944.39   633.9  969.39     644  977.08   694.3 1002.27   724.5 1021.52
   734.6 1031.67   764.8 1047.05   774.8 1051.11   815.1 1062.35   865.4 1069.34
#Mann= 3 , 0 , 0
    10.1     .08       0   261.7    .045       0   281.7     .08       0
Bank Sta=261.7,281.7
XS Rating Curve= 0 ,0
Exp/Cntr=0.3,0.1

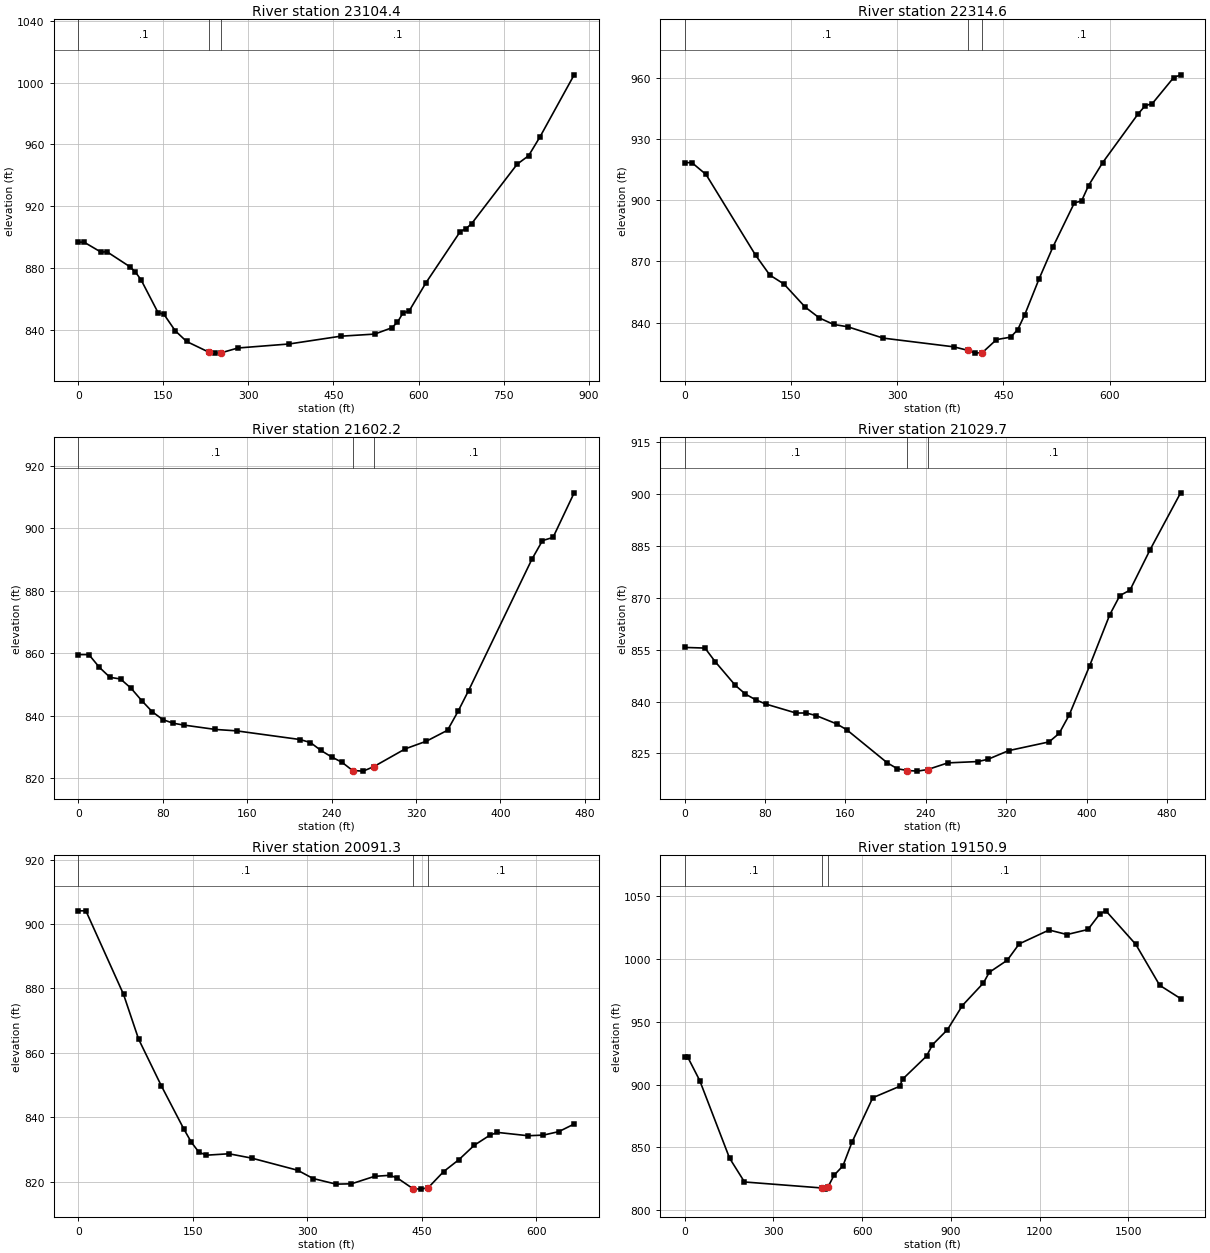
Type RM Length L Ch R = 1 ,23104.4 ,779.3,789.8,799.8
XS GIS Cut Line= 2
     1621462.013      345938.451      1621609.18       346800.48
#Sta/Elev= 30
       0  896.83    10.1  896.83    40.2  890.35    50.3  890.67    90.5  881.05
   100.5  877.58   110.6  872.51   140.7  851.21   150.8  850.29   170.9  839.55
     191  832.63   231.2  825.55   241.2   825.1   251.2  825.23   281.4  828.41
   371.9  831.02   462.4  836.03   522.7  837.41   552.8  841.47   562.9  845.11
   572.9  851.25     583  852.07   613.2  870.62   673.5  903.64   683.5  905.52
   693.6  908.77     774  947.25   794.1  952.68   814.2  964.87   874.5    1005
#Mann= 3 , 0 , 0
       0      .1       0   231.2    .045       0   251.2      .1       0
Bank Sta=231.2,251.2
XS Rating Curve= 0 ,0
Exp/Cntr=0.3,0.1

Type RM Length L Ch R = 1 ,22314.6 ,719,712.3,705.6
XS GIS Cut Line= 2
     1620994.926      345901.736     1620735.886      346552.395
#Sta/Elev= 30
       0  918.38      10  918.38      30  912.57     100  873.02   120.1  863.29
   140.1   858.9   170.1  847.59   190.1  842.28   210.1  839.12   230.1  837.97
   280.1  832.42   380.2  828.13   400.2  826.39   410.2  825.06   420.2   825.3
   440.2  831.68   460.2  832.89   470.2  836.54   480.2  843.93   500.2  861.28
   520.2  877.26   550.3  898.72   560.3  899.52   570.3  907.17   590.3  918.44
   640.3  942.28   650.3  946.26   660.3   947.3   690.3  959.98   700.3  961.39
#Mann= 3 , 0 , 0
       0      .1       0   400.2    .045       0   420.2      .1       0
Bank Sta=400.2,420.2
XS Rating Curve= 0 ,0
Exp/Cntr=0.3,0.1

Type RM Length L Ch R = 1 ,21602.2 ,577.4,572.5,567.8
XS GIS Cut Line= 2
     1620162.735      345995.562     1620138.258      346464.689
#Sta/Elev= 30
       0  859.51      10  859.51      20  855.41      30  852.23      40   851.7
      50  848.72      60   844.8      70  841.22      80   838.7      90  837.52
     100  836.94   129.9  835.54   149.9  835.09   209.9  832.32   219.9  831.35
   229.9  828.81   239.9  826.75   249.9     825   259.9  822.38   269.9  822.19
   279.9  823.62   309.8  829.33   329.8  831.78   349.8  835.28   359.8  841.35
   369.8  848.01   429.8  890.09   439.8  896.03   449.8  897.05   469.8  911.33
#Mann= 3 , 0 , 0
       0      .1       0   259.9    .045       0   279.9      .1       0
Bank Sta=259.9,279.9
XS Rating Curve= 0 ,0
Exp/Cntr=0.3,0.1

Type RM Length L Ch R = 1 ,21029.7 ,942.8,938.4,933.8
XS GIS Cut Line= 2
     1619571.226      345948.649     1619660.972      346434.094
#Sta/Elev= 30
       0  855.63    20.1  855.45    30.2  851.54    50.4  844.65    60.4  842.15
    70.5  840.52    80.6  839.28   110.8  836.68   120.9   836.7     131  835.92
   151.1  833.56   161.2  831.86   201.5  822.32   211.6  820.59   221.7  820.08
   231.7   819.9   241.7  820.35   261.9  822.28   292.2  822.67   302.2  823.36
   322.4  825.82   362.7  828.34   372.8  830.82   382.8  836.14     403  850.25
   423.1  865.05   433.2  870.61   443.3  872.19   463.4  883.91   493.7  900.29
#Mann= 3 , 0 , 0
       0      .1       0   221.7    .045       0   241.7      .1       0
Bank Sta=221.7,241.7
XS Rating Curve= 0 ,0
Exp/Cntr=0.3,0.1

Type RM Length L Ch R = 1 ,20091.3 ,943.2,940.3,936.8
XS GIS Cut Line= 3
     1618892.012      346297.435     1619077.623      346427.975
     1619258.891      346809.606
#Sta/Elev= 30
       0  904.09     9.9  904.09    59.2  878.15    78.9  864.26   108.5  849.84
   138.1  836.36     148  832.23   157.9  829.14   167.7   828.2   197.3  828.64
   226.9   827.3   287.3  823.52   307.4  820.96   337.6  819.21   357.7  819.31
   387.9  821.63     408  821.95     418  821.08   438.2  817.81   448.2  817.66
   458.2  818.09   478.4   823.1   498.5  826.82   518.6  831.29   538.8  834.38
   548.8  835.28   589.1  834.24   609.2  834.44   629.3  835.52   649.4  837.88
#Mann= 3 , 0 , 0
       0      .1       0   438.2    .045       0   458.2      .1       0
Bank Sta=438.2,458.2
XS Rating Curve= 0 ,0
Exp/Cntr=0.3,0.1

Type RM Length L Ch R = 1 ,19150.9 ,650.7,658.6,665.2
XS GIS Cut Line= 3
     1618598.297      346735.967     1618978.092       347343.64
     1619744.756      347922.524
#Sta/Elev= 30
       0  921.82    10.1  921.82    50.5  903.22   151.4  841.34   201.9  822.34
   464.4  817.54   474.4  816.63   484.4  818.35   504.6   827.6   534.9  835.17
   565.2  853.84   635.9  889.51   726.7   898.6   736.8  904.32   817.7  922.68
   837.9  931.78   888.5  943.77   939.1  963.06  1009.9  980.93  1030.1  989.55
  1090.8  999.15  1131.2  1012.2  1232.3 1023.27    1293 1019.65  1363.8 1023.68
  1404.2 1036.17  1424.5 1038.56  1525.6 1011.81  1606.5  979.17  1677.3  968.57
#Mann= 3 , 0 , 0
       0      .1       0   464.4    .045       0   484.4      .1       0
Bank Sta=464.4,484.4
XS Rating Curve= 0 ,0
Exp/Cntr=0.3,0.1

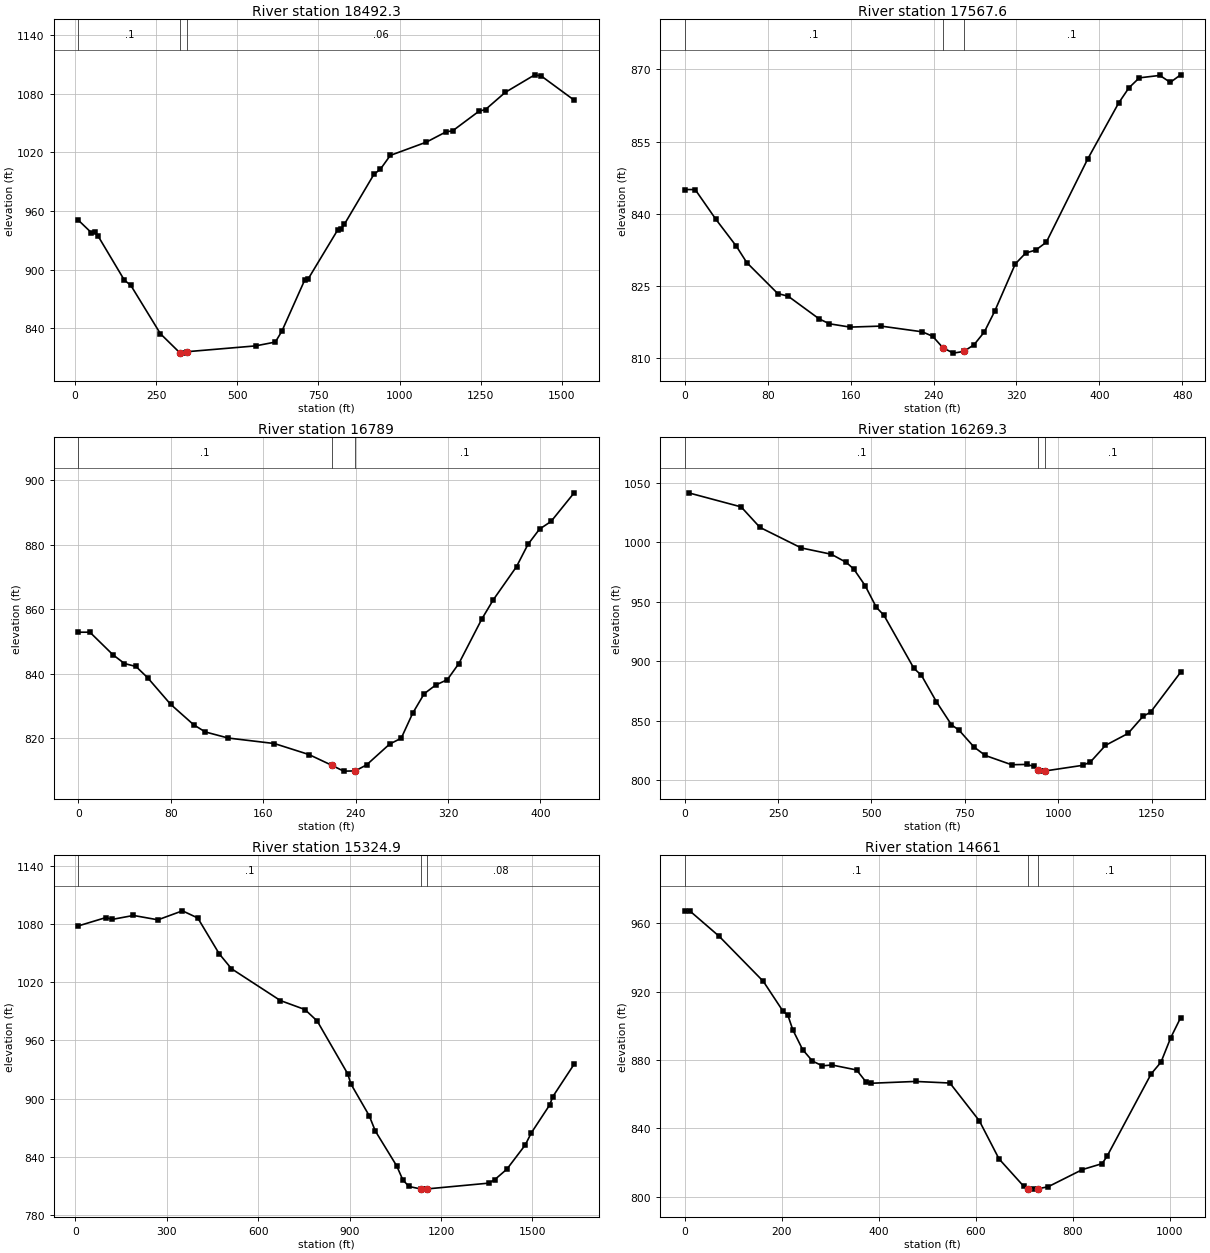
Type RM Length L Ch R = 1 ,18492.3 ,905.4,924.7,944.1
XS GIS Cut Line= 2
     1618236.268      346780.141     1618598.983      348275.069
#Sta/Elev= 30
    10.1  950.73    50.6  937.84    60.7  938.29    70.8  934.59   151.8  889.48
     172  883.99   263.1  834.57     324  814.75     334  814.74     344  816.17
   556.6  822.15   617.3  826.07   637.6  837.29   708.4  889.92   718.5  890.64
   809.6   940.8   819.8  941.94   829.9  946.43     921  997.52   941.2 1002.92
   971.6 1016.97  1082.9 1030.58  1143.6  1041.1  1163.8 1042.12  1244.8 1062.15
  1265.1 1063.93  1325.8 1081.42  1416.9  1099.4  1437.1 1098.15  1538.3 1073.49
#Mann= 3 , 0 , 0
    10.1      .1       0     324    .045       0     344     .06       0
Bank Sta=324,344
XS Rating Curve= 0 ,0
Exp/Cntr=0.3,0.1

Type RM Length L Ch R = 1 ,17567.6 ,779.8,778.5,777.2
XS GIS Cut Line= 2
     1617598.852      346984.808     1617282.701      347343.793
#Sta/Elev= 30
       0  845.06      10  845.06    29.9  838.91    49.8  833.28    59.8   829.9
    89.7  823.47    99.7  822.93   129.6  818.22   139.5   817.2   159.5  816.51
   189.3  816.72   229.2  815.53   239.2   814.6   249.1  812.21   259.1  811.11
   269.1  811.46     279  812.83     289   815.5     299   819.8   318.9  829.63
   328.9  831.88   338.8  832.52   348.8  834.13   388.7  851.38   418.6  863.02
   428.5  866.17   438.5  868.24   458.4  868.75   468.4   867.3   478.4  868.87
#Mann= 3 , 0 , 0
       0      .1       0   249.1    .045       0   269.1      .1       0
Bank Sta=249.1,269.1
XS Rating Curve= 0 ,0
Exp/Cntr=0.3,0.1

Type RM Length L Ch R = 1 ,16789   ,529.7,519.7,509.7
XS GIS Cut Line= 2
     1617115.447      346454.491     1616854.367      346795.118
#Sta/Elev= 30
       0  852.82      10  852.82    29.9  845.84    39.9   843.1    49.9  842.18
    59.9  838.73    79.8  830.48    99.8  824.11   109.8  821.88   129.7  819.98
   169.7  818.27   199.6  814.86   219.6  811.49   229.6  809.71   239.6  809.77
   249.5  811.64   269.5  818.11   279.5  819.92   289.4  827.66   299.4  833.74
   309.4  836.43   319.4  838.08   329.4   843.1   349.3  856.94   359.3  862.93
   379.3  873.16   389.2  880.07   399.2   884.8   409.2  887.19   429.2  896.07
#Mann= 3 , 0 , 0
       0      .1       0   219.6    .045       0   239.6      .1       0
Bank Sta=219.6,239.6
XS Rating Curve= 0 ,0
Exp/Cntr=0.3,0.1

Type RM Length L Ch R = 1 ,16269.3 ,972.5,944.4,916.9
XS GIS Cut Line= 2
     1616638.741      345495.193     1616460.106      346810.993
#Sta/Elev= 30
    10.1 1041.34   150.9 1029.53   201.2 1012.34   311.8   995.1   392.3  989.79
   432.6  982.93   452.7   977.3   482.9  963.48     513  945.22   533.2  938.63
   613.6  894.01   633.8  888.14     674  865.93   714.2  846.61   734.4  842.12
   774.6  827.97   804.8  820.88   875.2  813.11   915.4  813.36   935.5  811.72
   945.7  808.78   955.7  807.74   965.7  807.93  1066.3  812.64  1086.4  815.45
  1126.7  829.37    1187  839.35  1227.3  853.76  1247.4  857.21  1327.9  890.73
#Mann= 3 , 0 , 0
       0      .1       0   945.7    .045       0   965.7      .1       0
Bank Sta=945.7,965.7
XS Rating Curve= 0 ,0
Exp/Cntr=0.3,0.1

Type RM Length L Ch R = 1 ,15324.9 ,655.9,663.9,670.7
XS GIS Cut Line= 3
     1615237.781      345973.573     1615697.444      346644.945
     1616453.563      346970.115
#Sta/Elev= 30
      10 1077.98   100.5 1086.57   120.5 1084.65   190.9 1088.74   271.2 1084.25
   351.6 1093.51   401.8 1086.14   472.1  1049.3   512.3 1033.89     673 1001.07
   753.4  991.83   793.6  980.02     894   925.5     904  915.28   964.2  882.53
   984.3  866.73  1054.6  830.69  1074.6  816.34  1094.7  809.57  1134.9   806.9
  1144.9  806.83  1154.9  807.07  1355.7  812.98  1375.8  816.52  1415.9  827.36
  1476.1  852.26  1496.2   864.8  1556.4  893.55  1566.5  902.03  1636.7  935.58
#Mann= 3 , 0 , 0
      10      .1       0  1134.9    .045       0  1154.9     .08       0
Bank Sta=1134.9,1154.9
XS Rating Curve= 0 ,0
Exp/Cntr=0.3,0.1

Type RM Length L Ch R = 1 ,14661   ,768.2,764.4,760.3
XS GIS Cut Line= 2
       1615347.4      346646.239     1616016.057      347419.261
#Sta/Elev= 30
       0  967.38    10.1  967.38    70.8  952.48   161.9  926.06   202.4  908.62
   212.5  906.22   222.6  897.73   242.9  886.11   263.1  879.42   283.4  876.62
   303.6  877.09   354.2  874.18   374.4  866.88   384.5  866.41   475.6  867.47
   546.5  866.54   607.2   844.4   647.7  822.13   698.3  806.19   708.5  804.46
   718.5  804.41   728.5  804.66   748.9  805.79   819.7  815.87   860.2  819.33
   870.3  823.59   961.4  871.91   981.6  878.75  1001.8  893.13  1022.1  904.78
#Mann= 3 , 0 , 0
       0      .1       0   708.5    .045       0   728.5      .1       0
Bank Sta=708.5,728.5
XS Rating Curve= 0 ,0
Exp/Cntr=0.3,0.1

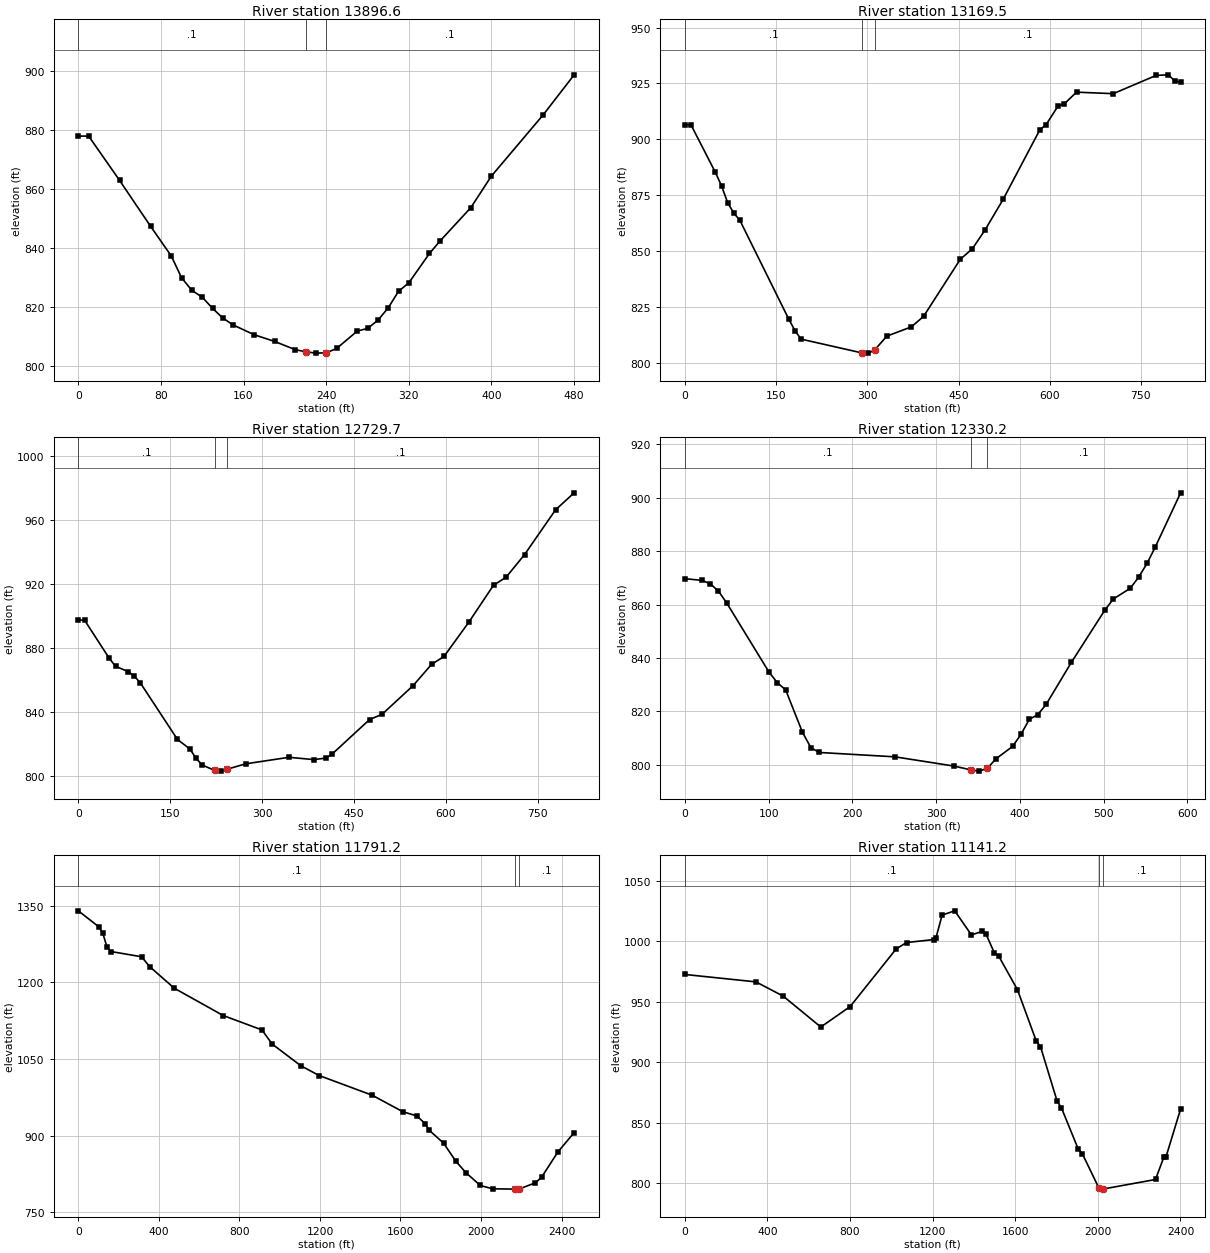
Type RM Length L Ch R = 1 ,13896.6 ,719.2,727.1,735.3
XS GIS Cut Line= 2
     1615141.033      347535.523     1615522.453      347827.198
#Sta/Elev= 30
       0  877.97      10  877.97      40  862.92      70  847.36      90  837.32
     100  829.92     110  825.63     120  823.34     130  819.56     140  816.24
   150.1   813.9   170.1  810.63   190.1  808.33   210.1  805.54   220.1  804.84
   230.1  804.37   240.1  804.48   250.1  805.94   270.1  811.84   280.1  812.75
   290.1  815.49   300.1  819.73   310.1  825.32   320.1  828.22   340.1  838.18
   350.1  842.32   380.1  853.69   400.1  864.43   450.2  885.17   480.2  898.74
#Mann= 3 , 0 , 0
       0      .1       0   220.1    .045       0   240.1      .1       0
Bank Sta=220.1,240.1
XS Rating Curve= 0 ,0
Exp/Cntr=0.3,0.1

Type RM Length L Ch R = 1 ,13169.5 ,429.6,439.8,449.9
XS GIS Cut Line= 2
     1614635.191       347878.19     1615033.489      348589.497
#Sta/Elev= 30
       0  906.49    10.1  906.49    50.3  885.17    60.4  879.15    70.5  871.56
    80.5  867.01    90.6   863.7   171.1  819.41   181.2  814.32   191.2  810.55
   291.9  804.35   301.9  804.29   311.9  805.62   332.1  811.88   372.4  816.03
   392.5   820.7   452.9  846.26     473  851.07   493.2  859.22   523.4   873.1
   583.7  904.23   593.8  906.46   613.9  914.95     624  915.87   644.1  921.07
   704.5   920.4     775  928.58   795.1  928.83   805.2  926.18   815.2  925.45
#Mann= 3 , 0 , 0
       0      .1       0   291.9    .045       0   311.9      .1       0
Bank Sta=291.9,311.9
XS Rating Curve= 0 ,0
Exp/Cntr=0.3,0.1

Type RM Length L Ch R = 1 ,12729.7 ,398.6,399.5,400.3
XS GIS Cut Line= 2
     1614349.635      347939.381      1614355.84      348748.944
#Sta/Elev= 30
       0  897.42    10.1  897.42    50.6  873.39    60.7  868.51      81  865.17
    91.1  862.41   101.2  858.09   161.9  822.59   182.2  816.62   192.3  810.74
   202.4  806.57   222.8  803.17   232.8  802.75   242.8  803.94   273.2  807.32
   344.1  811.42   384.6  809.97   404.8  810.96   414.9  813.63   475.6  835.09
   495.9  838.36   546.5   856.3   576.8  869.68   597.1  874.63   637.6  896.11
     678  919.34   698.3  924.22   728.6  938.48   779.2  966.53   809.6   977.2
#Mann= 3 , 0 , 0
       0      .1       0   222.8    .045       0   242.8      .1       0
Bank Sta=222.8,242.8
XS Rating Curve= 0 ,0
Exp/Cntr=0.3,0.1

Type RM Length L Ch R = 1 ,12330.2 ,529.8,539.1,548.3
XS GIS Cut Line= 2
     1613966.175      347853.714     1613947.817      348445.222
#Sta/Elev= 30
       0   869.7    20.1  869.07    30.1  867.83    40.1  865.08    50.2  860.49
   100.3  834.77   110.3  830.73   120.4     828   140.4  812.13   150.5  806.32
   160.5  804.54   250.8   802.9     321  799.45   341.1  798.04   351.1  797.54
   361.1  798.56   371.1  802.08   391.2   806.8   401.2  811.29   411.2  816.96
   421.3   818.7   431.3  822.56   461.4  838.32   501.5  857.97   511.6  862.12
   531.6  866.05   541.6  870.22   551.7  875.39   561.7  881.67   591.8  901.88
#Mann= 3 , 0 , 0
       0      .1       0   341.1    .045       0   361.1      .1       0
Bank Sta=341.1,361.1
XS Rating Curve= 0 ,0
Exp/Cntr=0.3,0.1

Type RM Length L Ch R = 1 ,11791.2 ,658.6,650,640.5
XS GIS Cut Line= 3
     1614554.994      346112.076     1614277.398      346499.026
     1613335.998      348248.072
#Sta/Elev= 30
       0 1339.74   101.3 1308.59   121.6 1296.03   141.9 1269.33   162.1 1260.11
   314.1 1249.81   354.6 1230.38   476.2 1188.35   719.4 1134.85     912 1106.62
   962.7 1079.03  1104.5 1036.66  1195.8 1017.44  1459.2   978.9  1611.3  946.65
  1682.2  938.21  1722.7  922.93    1743  910.16  1813.9  885.13  1874.7  849.79
  1925.4   827.1  1996.4  802.26  2057.2  795.73  2168.8  795.11  2178.8  795.09
  2188.8  795.14    2270  807.56  2300.4  818.14  2381.5  867.73  2462.5  905.75
#Mann= 3 , 0 , 0
       0      .1       0  2168.8    .045       0  2188.8      .1       0
Bank Sta=2168.8,2188.8
XS Rating Curve= 0 ,0
Exp/Cntr=0.3,0.1

Type RM Length L Ch R = 1 ,11141.2 ,500,496.4,492.8
XS GIS Cut Line= 3
     1612981.984      345742.843     1613109.827      346450.835
     1612868.825      348114.794
#Sta/Elev= 30
       0  972.61   344.5  966.47   476.3   954.7   658.6  929.11   800.5  946.01
  1023.3  993.72  1073.9  999.05  1205.6 1001.49  1215.7 1002.63  1246.1 1021.77
  1306.9 1025.28  1387.9 1005.33  1438.6  1008.2  1458.8 1005.86  1499.3  990.35
  1519.6  987.96  1610.7  959.99  1701.9  917.46  1722.2  912.91  1803.2  867.54
  1823.4  862.33  1904.5  828.29  1924.7  824.32  2005.9   795.5  2015.9  794.93
  2025.9  795.04  2279.2   802.9  2319.7  821.51  2329.9  821.56  2400.8  861.35
#Mann= 3 , 0 , 0
       0      .1       0  2005.9    .045       0  2025.9      .1       0
Bank Sta=2005.9,2025.9
XS Rating Curve= 0 ,0
Exp/Cntr=0.3,0.1

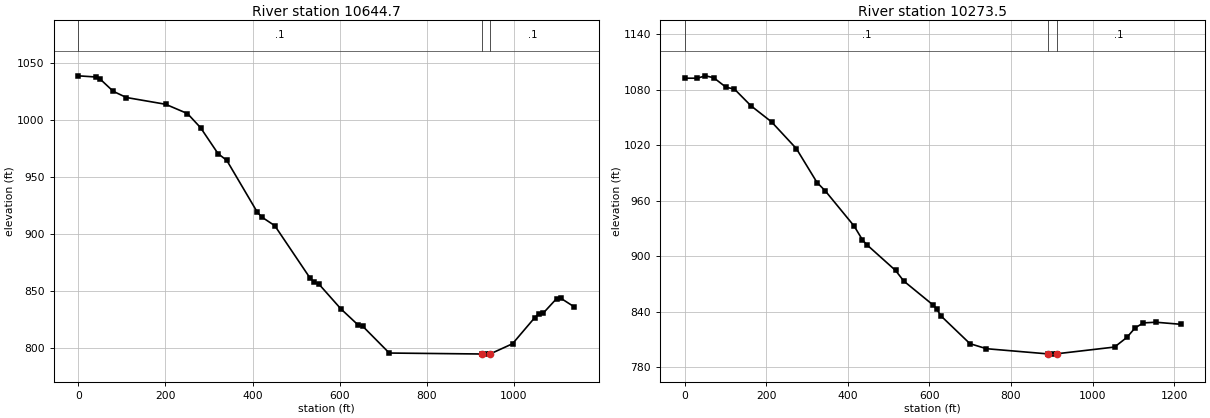
Type RM Length L Ch R = 1 ,10644.7 ,390.4,371.2,352
XS GIS Cut Line= 3
     1612392.651      346930.254     1612442.478      347378.698
     1612464.967      348065.841
#Sta/Elev= 30
       0 1038.67    40.1 1037.65    50.1 1035.79    80.2 1025.07   110.3 1019.64
   200.5 1013.69   250.7 1005.51   280.7  993.14   320.9  970.33   340.9  964.44
   411.1   918.9   421.1   914.7   451.2  907.08   532.1  861.13   542.2  857.22
   552.3  855.87   602.9  834.06   643.3  819.62   653.4   818.7   714.1  795.27
   926.5  794.42   936.5  794.31   946.5   794.6   997.2  803.44  1047.7  826.14
  1057.8  829.96  1067.9   830.4  1098.3  843.03  1108.4  843.29  1138.7  835.86
#Mann= 3 , 0 , 0
       0      .1       0   926.5    .045       0   946.5      .1       0
Bank Sta=926.5,946.5
XS Rating Curve= 0 ,0
Exp/Cntr=0.3,0.1

Type RM Length L Ch R = 1 ,10273.5 ,630.8,598.6,566.4
XS GIS Cut Line= 2
     1611356.246      347388.663     1612369.102      348061.762
#Sta/Elev= 30
       0 1092.43    30.4 1092.41    50.7 1094.99    70.9 1092.94   101.3 1082.58
   121.6 1080.73   162.1 1062.68   212.8 1045.22   273.6 1016.36   324.3  979.73
   344.6  970.66   415.5  932.55   435.8  917.71   445.9  912.73   516.8  884.74
   537.1  873.26   608.1  847.69   618.2  842.82   628.3  835.58   699.3  805.63
   739.8  800.16     892  794.49     902   794.3     912  794.67    1054  801.94
  1084.4  812.41  1104.6  822.74  1124.9  828.04  1155.3  828.76  1216.1  826.55
#Mann= 3 , 0 , 0
       0      .1       0     892    .045       0     912      .1       0
Bank Sta=892,912
XS Rating Curve= 0 ,0
Exp/Cntr=0.3,0.1