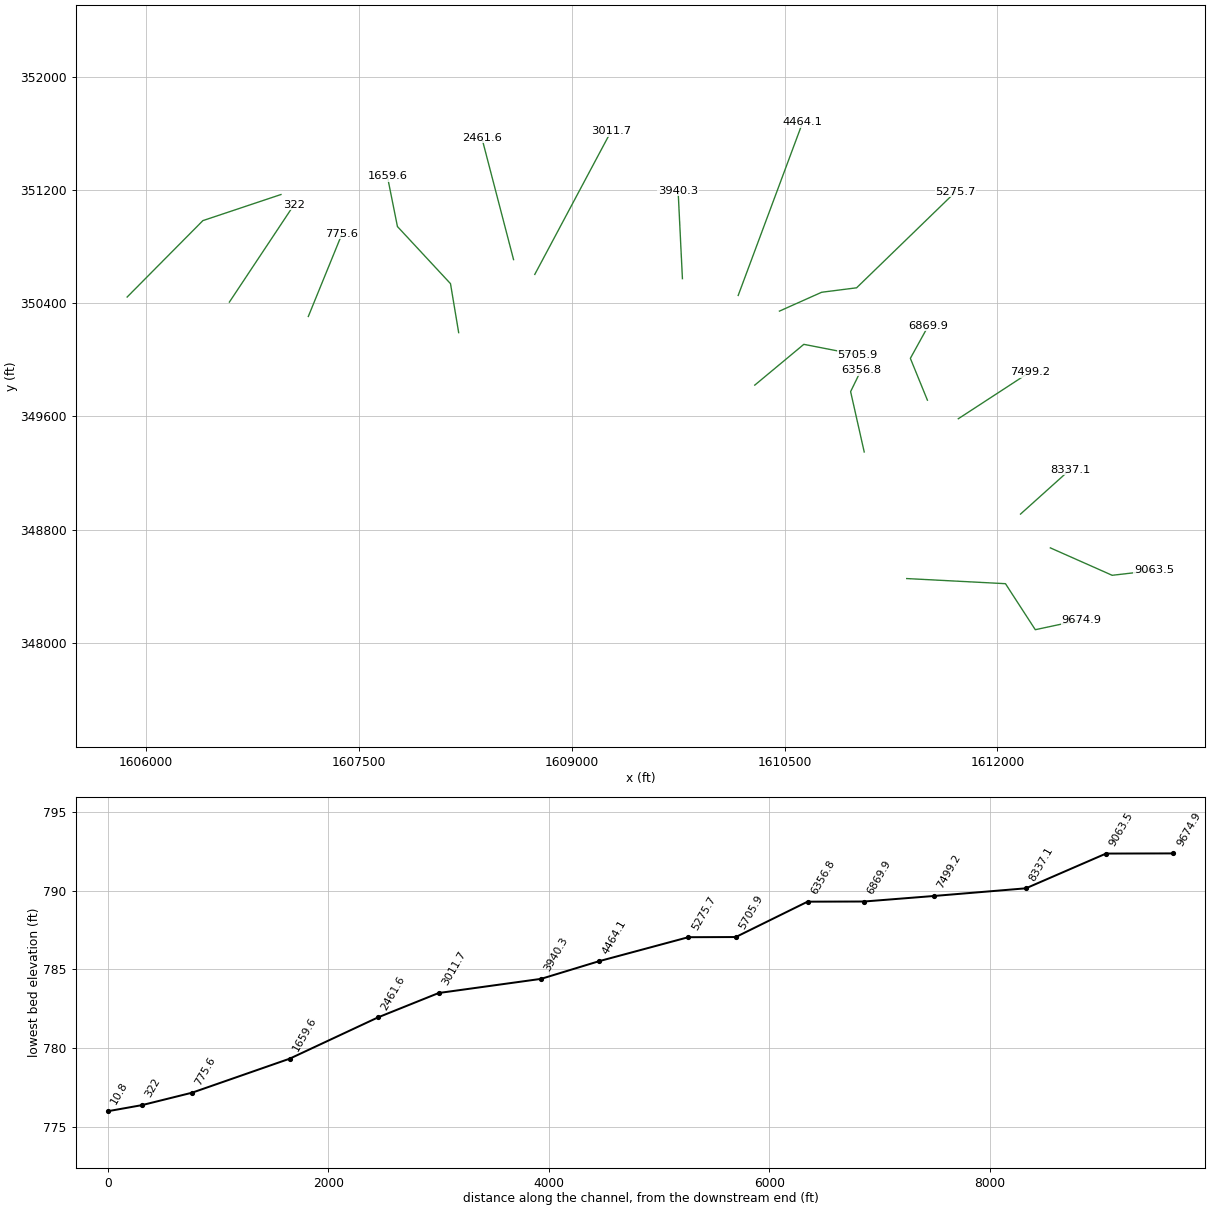
HEC-RAS study stfrktwl1.prj: stfrktwl1

--- stfrktwl1.g01 (geometry) --- (continued)

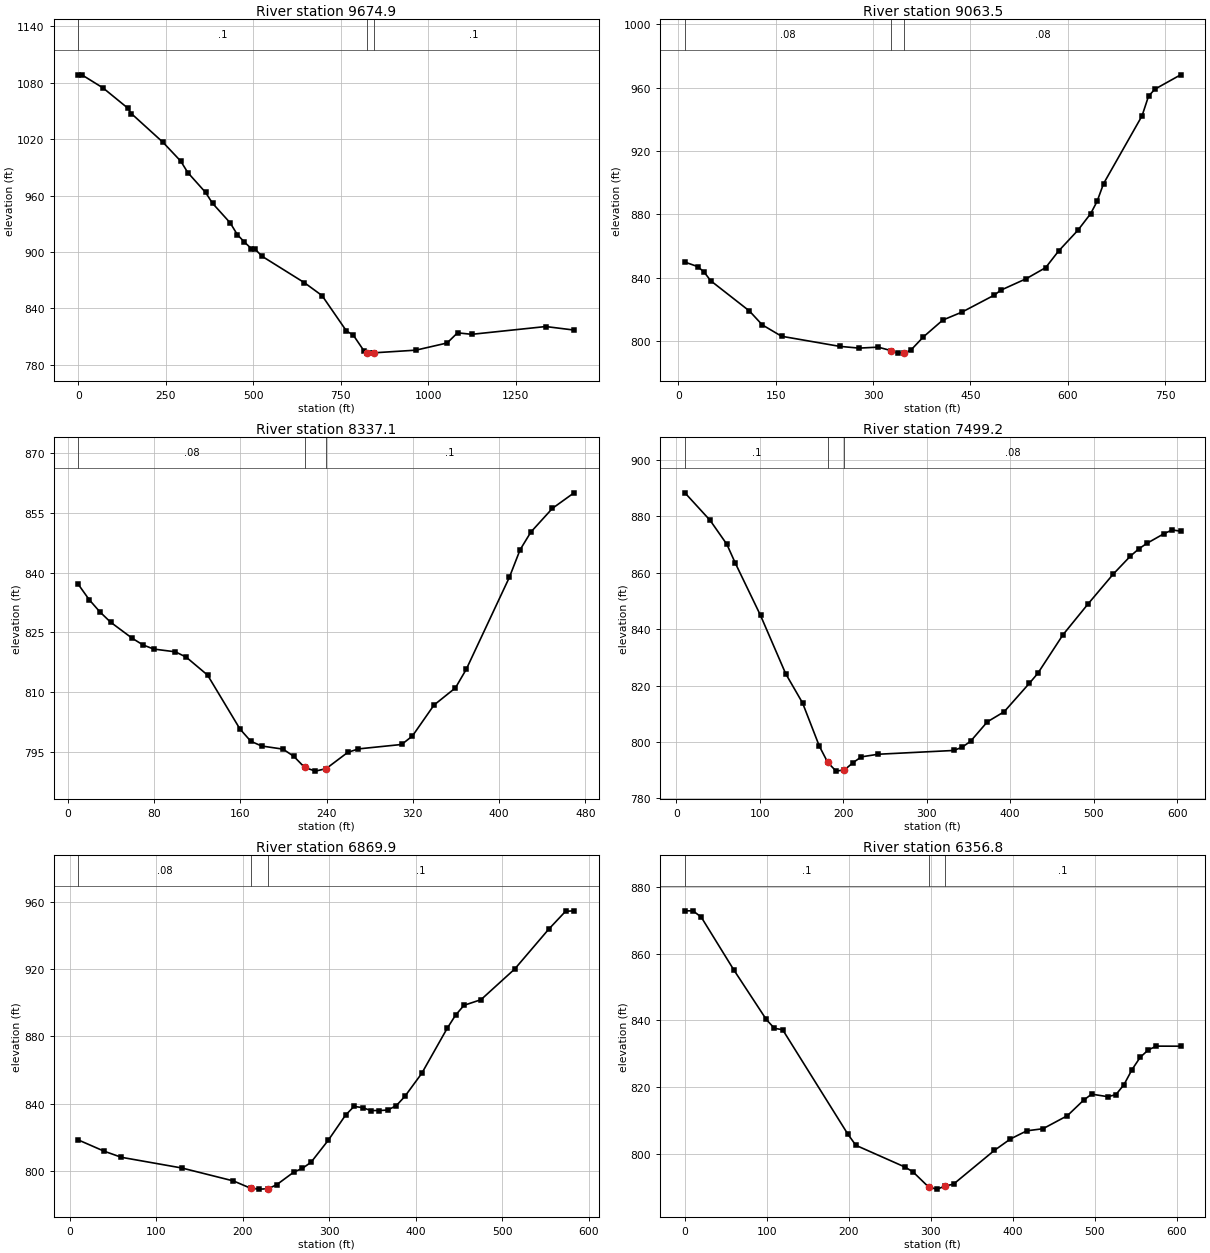
Type RM Length L Ch R = 1 ,9674.9  ,599.7,611.5,623.2
XS GIS Cut Line= 4
     1611361.229      348454.964     1612056.822      348418.799
     1612267.104      348093.817     1612592.636      348163.604
#Sta/Elev= 30
       0 1088.42    10.1 1088.42    70.7 1074.45   141.3 1053.02   151.4 1047.24
   242.3 1016.49   292.7  996.58   312.9   984.4   363.4  963.41   383.6  951.71
   434.1  930.88   454.3  918.46   474.4  910.56   494.6   903.5   504.7  903.11
   524.9  895.44   646.1  867.28   696.5  853.56     766  816.04   785.9  811.43
   815.6  795.14   825.5  792.55   835.5  792.38   845.5  792.73   964.5  795.53
  1053.8  803.17  1083.6  813.99    1124  812.38  1335.8  820.66  1416.5  816.91
#Mann= 3 , 0 , 0
       0      .1       0   825.5    .045       0   845.5      .1       0
Bank Sta=825.5,845.5
XS Rating Curve= 0 ,0
Exp/Cntr=0.3,0.1

Type RM Length L Ch R = 1 ,9063.5  ,704.4,726.4,748.4
XS GIS Cut Line= 3
     1612373.181      348671.627     1612808.887       348477.98
     1613104.019      348512.359
#Sta/Elev= 30
     9.9  849.84    29.8     847    39.7  843.42    49.7  838.06   109.3  818.98
   129.1  810.22   158.9  803.02   248.3  796.65   278.1  795.54   307.9  796.14
   327.7  793.94   337.7  792.37   347.7  792.62   357.6  794.05   377.5  802.64
   407.3  813.24   437.1  818.32   486.7     829   496.6  832.08   536.2  839.43
   565.9  846.37   585.7   856.8   615.5  869.94   635.3   880.5   645.2  888.26
   655.1   899.4   714.5  942.29   724.4  954.65   734.3  959.09   773.9  968.13
#Mann= 3 , 0 , 0
     9.9     .08       0   327.7    .045       0   347.7     .08       0
Bank Sta=327.7,347.7
XS Rating Curve= 0 ,0
Exp/Cntr=0.3,0.1

Type RM Length L Ch R = 1 ,8337.1  ,839.8,837.8,835.8
XS GIS Cut Line= 2
     1612163.094       348910.27      1612511.88      349224.381
#Sta/Elev= 30
      10  837.03      20  833.22      30  830.13    39.9  827.55    59.9  823.52
    69.9  821.84    79.9   820.8    99.9  820.11   109.9  818.79   129.8  814.26
   159.8  800.73   169.8  797.67   179.8  796.47   199.7  795.68   209.7  793.87
   219.7  791.09   229.7  790.16   239.7  790.79   259.7  794.87   269.6  795.74
   309.6  796.85   319.6  798.97   339.6  806.74   359.5  811.06   369.5  815.71
   409.5  838.83   419.4  845.72   429.4  850.17   449.4  856.13   469.4  860.02
#Mann= 3 , 0 , 0
      10     .08       0   219.7    .045       0   239.7      .1       0
Bank Sta=219.7,239.7
XS Rating Curve= 0 ,0
Exp/Cntr=0.3,0.1

Type RM Length L Ch R = 1 ,7499.2  ,601.4,629.3,657.1
XS GIS Cut Line= 2
     1611724.562      349583.366     1612230.403      349913.795
#Sta/Elev= 30
    10.1  888.25    40.3   878.5    60.4     870    70.5  863.34   100.7  844.83
   130.9  824.16   151.1  813.82   171.2  798.51   181.3  792.74   191.3  789.67
   201.3   790.1   211.5  792.65   221.5  794.72   241.7  795.65   332.3  796.99
   342.4  798.15   352.5  800.26   372.6  807.15   392.7   810.7   422.9  820.78
     433   824.3   463.2  837.97   493.4  848.95   523.6  859.51   543.8  865.77
   553.9  868.36   563.9  870.38   584.1  873.75   594.1  875.11   604.2  874.65
#Mann= 3 , 0 , 0
    10.1      .1       0   181.3    .045       0   201.3     .08       0
Bank Sta=181.3,201.3
XS Rating Curve= 0 ,0
Exp/Cntr=0.3,0.1

Type RM Length L Ch R = 1 ,6869.9  ,516.5,513.1,509.7
XS GIS Cut Line= 3
      1611506.95      349714.481     1611386.779      350009.876
     1611514.174      350241.189
#Sta/Elev= 30
      10  818.51    39.9  811.82    59.8  808.21   129.6  801.87   189.3  794.18
   209.2  789.85   219.2  789.32   229.2  789.52   239.2  791.91   259.1  799.43
   269.1  801.69     279  805.26     299  818.39   318.9  833.24   328.7  838.43
   338.5  837.69   348.2  835.97     358  835.96   367.8  836.27   377.6  838.91
   387.4  844.33   406.9  857.98   436.3  884.71     446  892.54   455.8  898.43
   475.4  901.76   514.5  920.01   553.6  943.53   573.2  954.23     583  954.51
#Mann= 3 , 0 , 0
      10     .08       0   209.2    .045       0   229.2      .1       0
Bank Sta=209.2,229.2
XS Rating Curve= 0 ,0
Exp/Cntr=0.3,0.1

Type RM Length L Ch R = 1 ,6356.8  ,690.7,650.9,611.1
XS GIS Cut Line= 3
     1611061.665      349348.802     1610965.799      349775.096
     1611039.228      349926.033
#Sta/Elev= 30
       0  872.88     9.9  872.88    19.9  870.99    59.6  855.16    99.3  840.25
   109.2  837.59   119.2  837.19   198.6  805.89   208.5  802.48   268.1  795.98
   278.1  794.53   297.8  789.83   307.8  789.31   317.8  790.26   327.7  790.81
   377.4  800.91   397.2  804.38   417.1  806.82   436.9  807.45   466.6  811.36
   486.3  815.99   496.2  817.83   515.9  817.07   525.8  817.67   535.7  820.69
   545.5  825.21   555.4  828.87   565.3  831.11   575.2  832.25   604.8  832.23
#Mann= 3 , 0 , 0
       0      .1       0   297.8    .045       0   317.8      .1       0
Bank Sta=297.8,317.8
XS Rating Curve= 0 ,0
Exp/Cntr=0.3,0.1

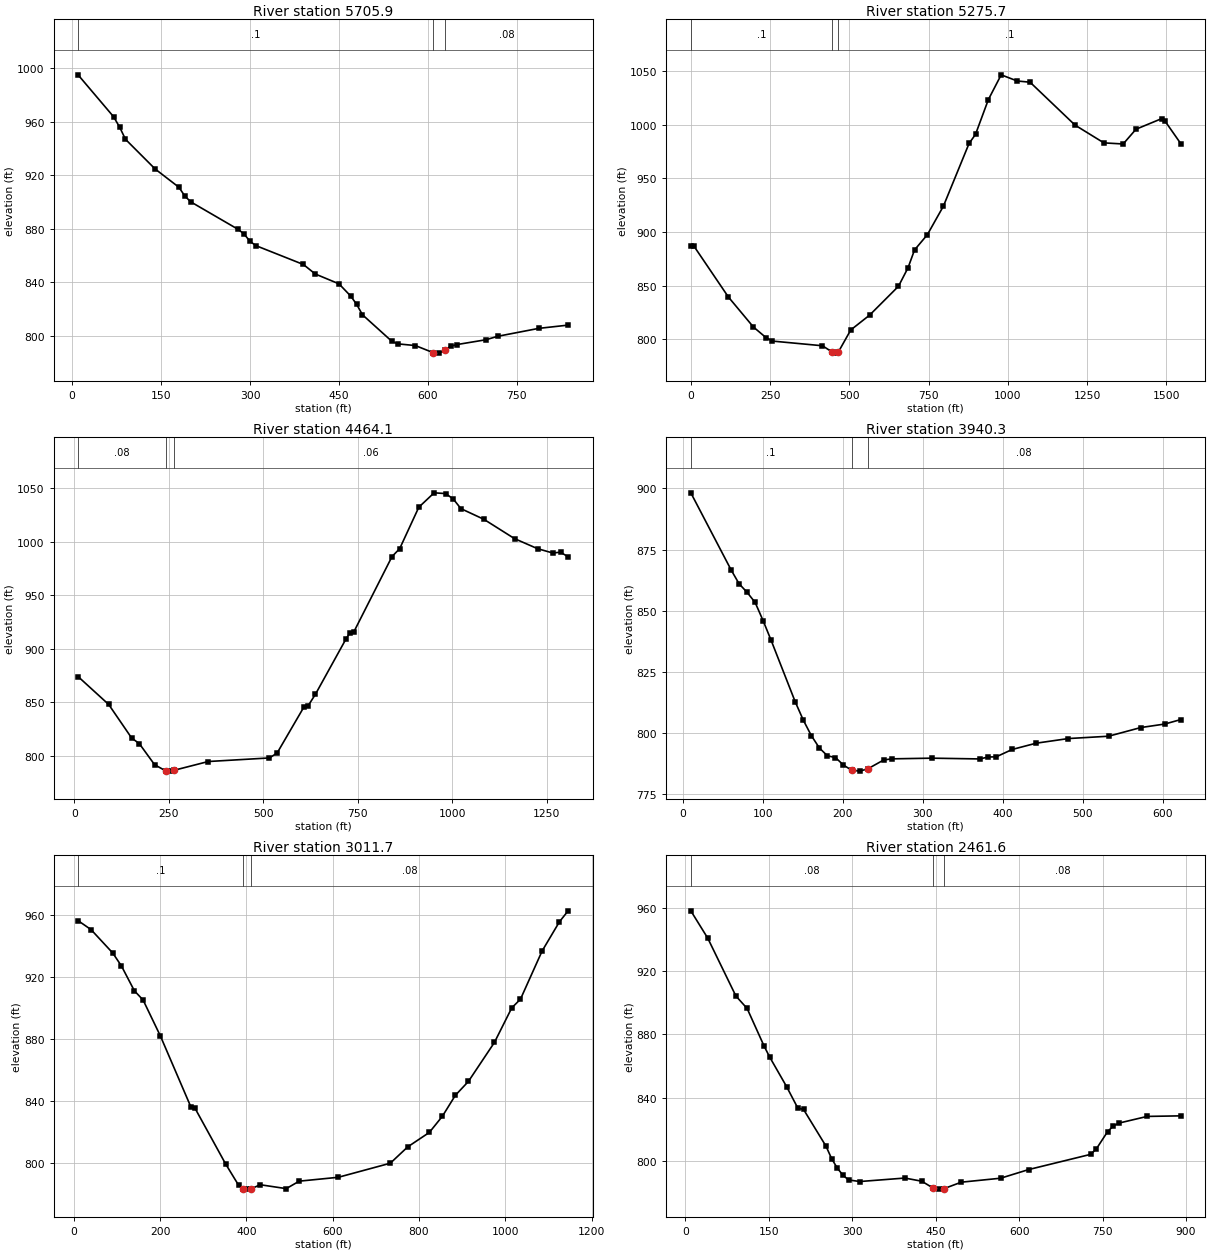
Type RM Length L Ch R = 1 ,5705.9  ,423.9,430.3,436.7
XS GIS Cut Line= 3
     1610290.434      349820.846     1610636.172      350108.839
     1611015.479       350034.79
#Sta/Elev= 30
      10  995.18      70  963.79      80  956.16      90  946.96     140  924.76
     180  911.12     190  904.59     200   900.2     280  879.59     290  876.12
     300  870.63     310  867.43     390  853.34     410  846.24     450  838.87
   469.8  829.72   479.7   823.6   489.6  815.74   539.2  795.87   549.1  793.99
   578.8  792.72   608.4  787.49   618.4  787.06   628.4  789.38   638.3  792.22
   648.2  793.41   697.7  797.06   717.5  799.63   786.9  805.58   836.4  808.01
#Mann= 3 , 0 , 0
      10      .1       0   608.4    .045       0   628.4     .08       0
Bank Sta=608.4,628.4
XS Rating Curve= 0 ,0
Exp/Cntr=0.3,0.1

Type RM Length L Ch R = 1 ,5275.7  ,789.8,811.6,833.3
XS GIS Cut Line= 4
     1610464.341      350343.413     1610761.819      350476.612
     1611007.937      350508.005     1611705.037      351185.491
#Sta/Elev= 30
       0  886.83     9.9  886.83   118.5  839.41   197.5   811.4     237  801.57
   256.8  798.31   415.3  793.92     445  788.24     455  787.05     465  787.87
   504.6  808.67   564.1  822.52   655.1  849.42   685.4  866.79   705.7  883.29
   746.2  897.53   796.8  924.15   877.8  982.67   898.1  991.12   938.6 1023.54
   979.1 1046.68  1029.7 1040.93  1070.2  1039.8    1212  999.79  1303.1   983.2
  1363.9  982.16  1404.4  995.93  1485.4 1005.82  1495.5 1003.71  1546.1  982.32
#Mann= 3 , 0 , 0
       0      .1       0     445    .045       0     465      .1       0
Bank Sta=445,465
XS Rating Curve= 0 ,0
Exp/Cntr=0.3,0.1

Type RM Length L Ch R = 1 ,4464.1  ,515.5,523.8,532.1
XS GIS Cut Line= 2
     1610173.646      350454.107      1610628.77       351678.78
#Sta/Elev= 30
    10.1  873.89    91.2  847.78   151.9  816.45   172.2   811.2   212.7  791.47
   243.2  785.54   253.2  785.52   263.2  786.22   354.5   794.5   516.5  797.85
   536.8  802.49   607.7   845.5   617.8  846.08   638.1  857.36   719.1  909.15
   729.2  914.64   739.3  915.39   840.6  985.98   860.9  993.38   911.5 1032.09
     952 1045.54   982.4 1044.85  1002.7 1039.76  1022.9 1030.76  1083.7 1020.79
  1164.7 1002.75  1225.5  993.37    1266  989.31  1286.3  990.08  1306.5  985.73
#Mann= 3 , 0 , 0
    10.1     .08       0   243.2    .045       0   263.2     .06       0
Bank Sta=243.2,263.2
XS Rating Curve= 0 ,0
Exp/Cntr=0.3,0.1

Type RM Length L Ch R = 1 ,3940.3  ,940.5,928.6,917.6
XS GIS Cut Line= 2
     1609780.743      350572.613     1609750.148      351194.716
#Sta/Elev= 30
      10  898.19    60.3  866.72    70.3  861.03    80.4  857.49    90.4  853.38
   100.5  845.85   110.5  837.82   140.6  812.71   150.7  805.23   160.7  798.93
   170.8  793.85   180.8  790.67   190.9  789.95   200.9  786.88     211   784.8
     221   784.4     231  785.28   251.2  788.96   261.2  789.42   311.4   789.7
   371.7  789.38   381.8  790.19   391.8  790.23   411.9  793.26     442  795.83
   482.2  797.72   532.4  798.67   572.6  802.21   602.8  803.66   622.9   805.5
#Mann= 3 , 0 , 0
      10      .1       0     211    .045       0     231     .08       0
Bank Sta=211,231
XS Rating Curve= 0 ,0
Exp/Cntr=0.3,0.1

Type RM Length L Ch R = 1 ,3011.7  ,534,550.1,565.3
XS GIS Cut Line= 2
     1608740.322      350602.514     1609278.455      351614.005
#Sta/Elev= 30
    10.1  956.36    40.2  950.58    90.5  935.52   110.6  927.19   140.7  911.16
   160.8  905.26     201  882.04   271.4  836.51   281.4  835.43   351.8  799.83
   381.9  786.11     392  783.86     402   783.5     412  783.81   432.2  786.33
   492.5  783.82   522.6  788.63   613.1  791.12   733.7  800.19   773.9  810.68
   824.1     820   854.3  830.41   884.4   843.9   914.6  852.83   974.9  877.94
  1015.1  900.21  1035.2  905.76  1085.4  936.82  1125.6  955.64  1145.7  962.67
#Mann= 3 , 0 , 0
    10.1      .1       0     392    .045       0     412     .08       0
Bank Sta=392,412
XS Rating Curve= 0 ,0
Exp/Cntr=0.3,0.1

Type RM Length L Ch R = 1 ,2461.6  ,792.6,802,811.4
XS GIS Cut Line= 2
      1608590.84      350707.151     1608366.618       351569.16
#Sta/Elev= 30
    10.1  958.36    40.5  941.04    91.1  904.36   111.3  896.45   141.7  872.67
   151.8  865.66   182.2  846.92   202.4  833.28   212.6  832.49     253  809.16
   263.2  801.21   273.3  795.27   283.4  790.79   293.5  787.78   313.8  786.77
   394.7  788.97   425.1  786.96   445.5  782.61   455.5  781.95   465.5  782.32
     496  786.35   566.8  788.87   617.4  794.38   728.7  804.01   738.9  807.53
   759.1  818.46   769.2  821.94   779.4  823.81     830  828.04   890.7   828.4
#Mann= 3 , 0 , 0
    10.1     .08       0   445.5    .045       0   465.5     .08       0
Bank Sta=445.5,465.5
XS Rating Curve= 0 ,0
Exp/Cntr=0.3,0.1

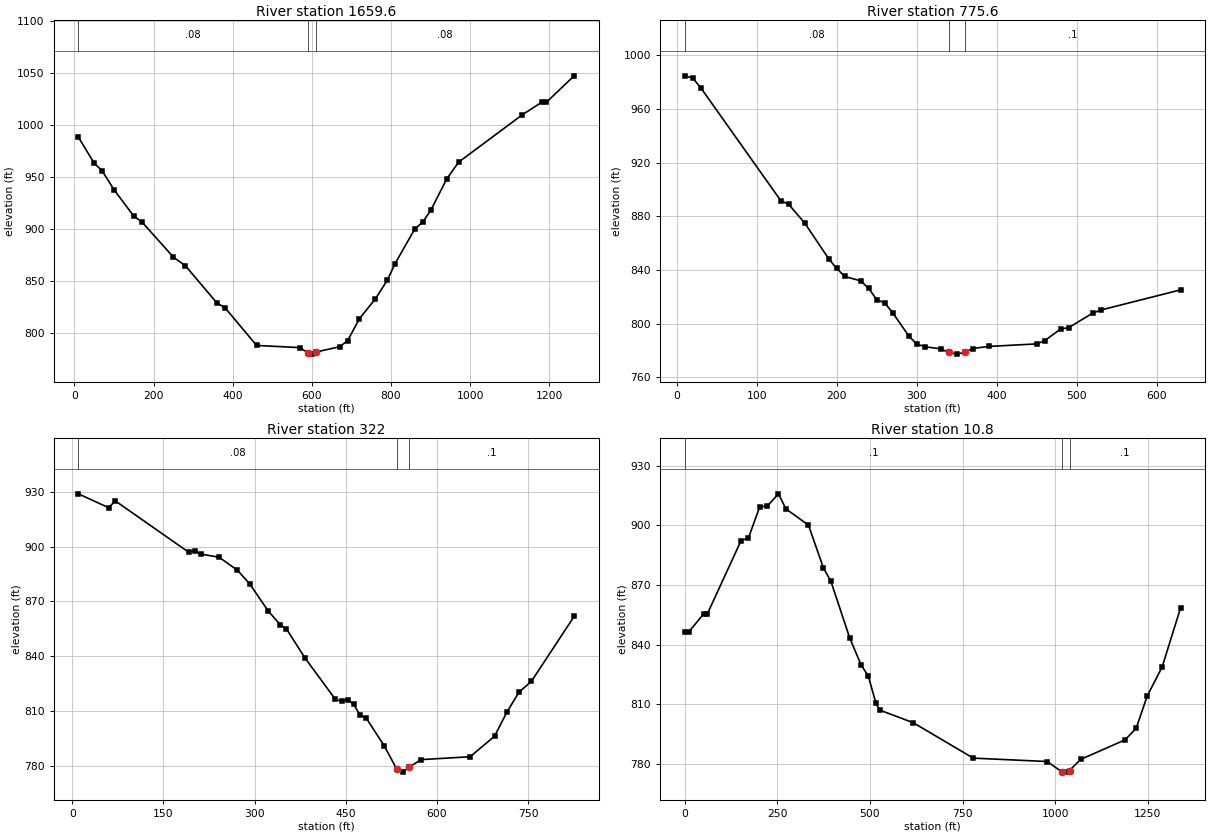
Type RM Length L Ch R = 1 ,1659.6  ,906.2,884,861.9
XS GIS Cut Line= 4
     1608204.073      350191.482       1608146.5      350537.318
      1607772.61      350940.615      1607701.49      351296.217
#Sta/Elev= 30
      10  988.14    50.1  962.96    70.1  955.68   100.2  937.48   150.3  911.95
   170.3  906.63   250.4  872.58   280.5  864.38   360.6   828.4   380.6  823.99
   460.6  787.67   570.6  785.58   590.6  780.44   600.6  779.32   610.6  781.36
   670.6  786.41   690.6  792.29   720.6  813.52   760.6  832.37   790.6  850.22
   810.6  866.44   860.5  899.76   880.5  906.33   900.5  917.49   940.8  947.61
   971.1  963.97  1132.2 1009.55  1182.6 1021.94  1192.7 1021.48  1263.2 1047.02
#Mann= 3 , 0 , 0
      10     .08       0   590.6    .045       0   610.6     .08       0
Bank Sta=590.6,610.6
XS Rating Curve= 0 ,0
Exp/Cntr=0.3,0.1

Type RM Length L Ch R = 1 ,775.6   ,457.6,453.6,449.6
XS GIS Cut Line= 2
     1607144.643      350305.596     1607381.934      350888.652
#Sta/Elev= 30
      10  984.77      20  983.04      30  975.82   129.9  891.67   139.9  888.84
   159.9   874.9   189.8  848.28   199.8  841.08   209.8  835.09   229.8  831.81
   239.8   826.2   249.8  817.79   259.8   815.3   269.8  808.01   289.8  790.71
   299.8  784.73   309.8  782.68   329.7   781.1   339.7  778.48   349.7  777.16
   359.7  778.49   369.7  781.35   389.7  782.89   449.6  784.79   459.6  787.17
   479.6   795.9   489.6  796.92   519.6  807.72   529.6  810.01   629.5  825.11
#Mann= 3 , 0 , 0
      10     .08       0   339.7    .045       0   359.7      .1       0
Bank Sta=339.7,359.7
XS Rating Curve= 0 ,0
Exp/Cntr=0.3,0.1

Type RM Length L Ch R = 1 ,322     ,324.9,311.2,297.5
XS GIS Cut Line= 2
     1606588.538       350407.19     1607044.934      351095.674
#Sta/Elev= 30
    10.1     929    60.4  921.33    70.5  925.22   191.4  897.04   201.5  897.78
   211.5  895.97   241.8   894.2     272  887.06   292.1  879.62   322.3  864.86
   342.5  857.14   352.6   854.9   382.8  839.09   433.2  816.23   443.2  815.22
   453.3  816.12   463.4  813.55   473.5   807.6   483.5  806.19   513.7  790.66
     534  778.06     544  776.37     554     779   574.2  783.23   654.8  784.81
   695.1  796.09   715.2  809.21   735.4   820.3   755.5  826.08     826  861.79
#Mann= 3 , 0 , 0
    10.1     .08       0     534    .045       0     554      .1       0
Bank Sta=534,554
XS Rating Curve= 0 ,0
Exp/Cntr=0.3,0.1

Type RM Length L Ch R = 1 ,10.8    ,2.4,10.8,19.2
XS GIS Cut Line= 3
     1605868.018      350442.834     1606401.752       350982.44
     1606951.821      351166.713
#Sta/Elev= 30
       0   846.3    10.1   846.3    50.6  855.49    60.7  855.46   151.8  892.32
     172  893.78   202.4  909.41   222.6  909.71     253  915.91   273.2  908.32
     334  900.17   374.4  878.65   394.7  871.86   445.3  843.51   475.6  830.08
   495.9  824.13   516.1  810.69   526.2  807.19   617.3   800.8     779  783.02
     979  781.31    1019  776.03    1029  775.98    1039  776.79    1069  782.37
  1189.1  792.21  1219.1  798.07  1249.1  814.36  1289.1  828.82  1339.1  858.65
#Mann= 3 , 0 , 0
       0      .1       0    1019    .045       0    1039      .1       0
Bank Sta=1019,1039
XS Rating Curve= 0 ,0
Exp/Cntr=0.3,0.1
Stream Node=stfrktwl1       ,Main            , 0 , 0 ,Upstream end
Stream Node=stfrktwl1       ,Main            , 0 , 1 ,Downstream end

Chan Stop Cuts=-1
Use User Specified Reach Order=0